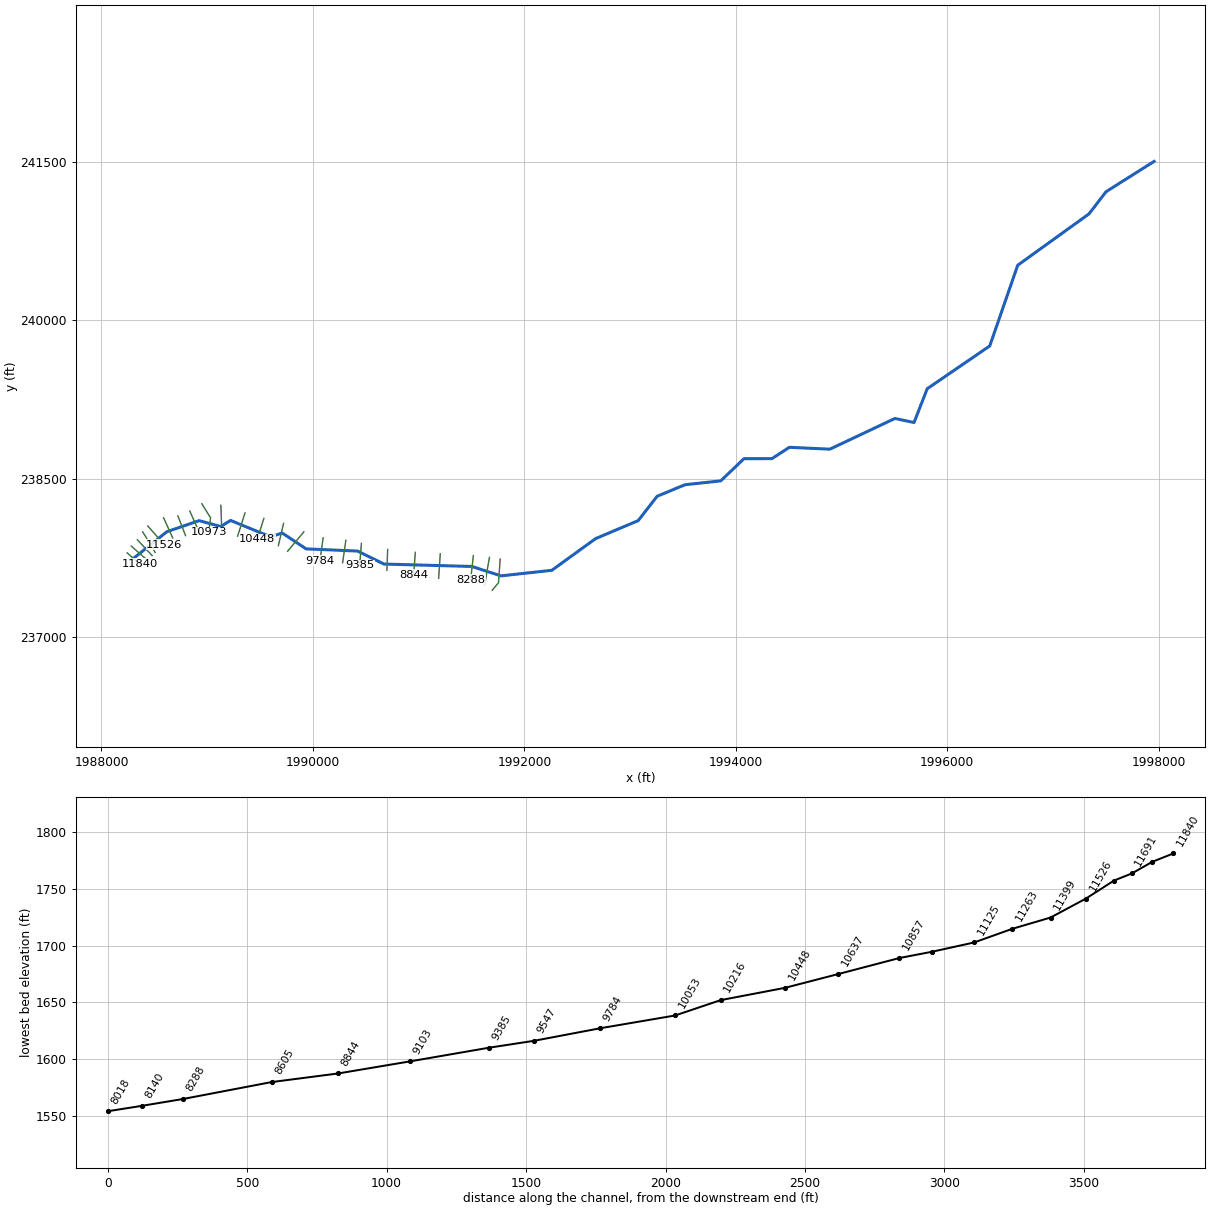
--- BEECHRN.prj (project) ---

Proj Title=BEECHRN
Current Plan=p01
Default Exp/Contr=0,0
English Units
Geom File=g01
Flow File=f01
Plan File=p01
BEGIN DESCRIPTION:
Stream Name: Beech Run
Flood Zone: Detailed
Summers County, West Virginia
HEC-RAS Version: 5.0.7
Hydrology Method: Regression
Model Notes:
END DESCRIPTION:
DSS Export Rating Curves= 0
DSS Export Rating Curve Sorted= 0
DSS Export Volume Flow Curves= 0
DXF OffsetX= 0
DXF OffsetY= 0
DXF ScaleX= 0
DXF ScaleY= 0

--- BEECHRN.p01 (plan) ---

Plan Title=Floodplain
Program Version=5.07
Short Identifier=Floodplain
Geom File=g01
Flow File=f01
Subcritical Flow
K Sum by GR= 0
Std Step Tol= 0.01
Critical Tol= 0.01
Num of Std Step Trials= 20
Max Error Tol= 0.3
Flow Tol Ratio= 0.001
Split Flow NTrial= 30
Split Flow Tol= 0.02
Split Flow Ratio= 0.02
Log Output Level= 0
Friction Slope Method= 1
Unsteady Friction Slope Method= 2
Unsteady Bridges Friction Slope Method= 1
Parabolic Critical Depth
Global Vel Dist= 0 , 0 , 0
Global Log Level= 0
CheckData=True
Encroach Param=-1 ,5,5, 2
Encroach River=BEECHRN
Encroach Reach=Main
Encroach Node=11840
       1    68.7    91.9
Encroach Node=11764
       1    93.8   114.7
Encroach Node=11691
       1    98.7   117.3
Encroach Node=11627
       1   148.1   172.3
Encroach Node=11526
       1  149.85     179
Encroach Node=11399
       1   130.9   153.1
Encroach Node=11263
       1   137.1   161.1
Encroach Node=11125
       1     103   124.8
Encroach Node=10973
       1     209   240.4
Encroach Node=10857
       1   187.7   211.1
Encroach Node=10637
       1     115   142.7
Encroach Node=10448
       1     120   143.9
Encroach Node=10216
       1    86.3   110.1
Encroach Node=10053
       1   117.4   145.4
Encroach Node=9784
       1   118.9   148.5
Encroach Node=9547
       1   103.6   131.5
Encroach Node=9385
       1    67.8    89.7
Encroach Node=9103
       1   113.3     149
Encroach Node=8844
       1   109.8   133.6
Encroach Node=8605
       1   115.1   144.8
Encroach Node=8288
       1    95.9   122.2
Encroach Node=8140
       1   124.7   150.9
Encroach Node=8018
       1  143.75   164.2
Encroach Node=7987
       1  143.85  164.32
Encroach Node=7817
       1   95.05   118.8
Encroach Node=7651
       1   112.4   139.6
Encroach Node=7526
       1   121.6     144
Encroach Node=7448
       1  112.28   133.3
Encroach Node=7402
       1   122.7   136.5
Encroach Node=7316
       1  159.13   191.6
Encroach Node=7244
       1   201.5     229
Encroach Node=7192
       1   213.5   227.2
Encroach Node=7131
       1     203   225.4
Encroach Node=7081
       1  164.25  183.95
Encroach Node=7038
       1   168.5   186.8
Encroach Node=6877
       1   158.8   185.1
Encroach Node=6671
       1   145.3   173.4
Encroach Node=6448
       1   133.1   160.3
Encroach Node=6278
       1    63.7    90.3
Encroach Node=5986
       1   118.5     161
Encroach Node=5740
       1   127.6     155
Encroach Node=5530
       1   130.1   154.3
Encroach Node=5375
       1   124.6   152.5
Encroach Node=5270
       1   177.8   212.5
Encroach Node=5178
       1   267.5   294.6
Encroach Node=5042
       1  178.65   216.2
Encroach Node=4868
       1   112.8  146.87
Encroach Node=4730
       1      82     116
Encroach Node=4527
       1   97.89     156
Encroach Node=4353
       1     113     147
Encroach Node=4237
       1     120     164
Encroach Node=4215
       1     123   167.6
Encroach Node=4202
       1     130     165
Encroach Node=4170
       1     137     160
Encroach Node=4021
       1   101.5   137.8
Encroach Node=3941
       1      86     120
Encroach Node=3906
       1    89.1   113.8
Encroach Node=3799
       1    79.1     103
Encroach Node=3604
       1   188.5   224.3
Encroach Node=3415
       1      70   102.3
Encroach Node=3292
       1    91.5     120
Encroach Node=3142
       1    78.1     108
Encroach Node=2996
       1    76.8   104.4
Encroach Node=2945
       1     126     190
Encroach Node=2889
       1   139.3   164.2
Encroach Node=2726
       1   139.5   168.2
Encroach Node=2533
       1   189.3   213.1
Encroach Node=2418
       1     165   193.1
Encroach Node=2328
       1     135   155.7
Encroach Node=2120
       1    76.9   107.4
Encroach Node=1995
       1    70.2    95.4
Encroach Node=1976
       1      69      92
Encroach Node=1888
       1    65.5    96.2
Encroach Node=1771
       1      58    78.2
Encroach Node=1622
       1    43.5      78
Encroach Node=1430
       1     106   130.5
Encroach Node=1216
       1   131.7   156.8
Encroach Node=1031
       1    82.5   104.2
Encroach Node=833
       1   131.8   155.1
Encroach Node=695
       1   105.8   125.8
Encroach Node=537
       1   143.1     167
Encroach Node=423
       1   192.8  203.85
Encroach Node=210
       1   188.5   220.5
Encroach Node=127
       1   103.6   440.9
Mapping Interval=1HOUR
Computation Time Step Use Courant=        0
Computation Time Step Use Time Series=    0
Computation Time Step Count To Double=0
Computation Time Step Max Doubling=0
Computation Time Step Max Halving=0
Computation Time Step Residence Courant=0
Run HTab= 0
Run UNet= 0
Run Sediment= 0
Run PostProcess= 0
Run WQNet= 0
Run RASMapper= 0
UNET Theta= 0
UNET Theta Warmup= 0
UNET ZTol= 0
UNET ZSATol= 0
UNET MxIter= 0
UNET Max Iter WO Improvement= 0
UNET MaxInSteps= 0
UNET DtIC= 0
UNET DtMin= 0
UNET MaxCRTS= 0
UNET WFStab= 0
UNET SFStab= 0
UNET WFX= 1
UNET SFX= 1
UNET 1D Methodology=Finite Difference
UNET DSS MLevel= 1
UNET Pardiso=0
UNET DZMax Abort= 0
UNET Use Existing IB Tables= 0
UNET Froude Reduction=False
UNET Froude Limit= 0
UNET Froude Power= 0
UNET D1 Cores= 0
UNET D2 Coriolis=0
UNET D2 Cores= 0
UNET D2 Theta= 1
UNET D2 Theta Warmup= 1
UNET D2 Z Tol= 0.01
UNET D2 Volume Tol= 0.01
UNET D2 Max Iterations= 20
UNET D2 Equation= 0
UNET D2 RampUpFraction=0.1
UNET D2 TimeSlices= 1
UNET D2 BCVolumeCheck=0
UNET D1D2 MaxIter= 0
UNET D1D2 ZTol=0.01
UNET D1D2 QTol=0.1
UNET D1D2 MinQTol=1
Write IC File= 0
Write IC File at Fixed DateTime=0
Write IC File at Sim End=0
Echo Input=False
Echo Parameters=False
Echo Output=False
Write Detailed= 0
HDF Write Warmup=0
HDF Write Time Slices=0
HDF Flush=0
HDF Face Node Velocities=0
HDF Compression= 1
HDF Chunk Size= 1
HDF Spatial Parts= 1
HDF Use Max Rows=0
HDF Fixed Rows= 1
Calibration Method= 0
Calibration Iterations= 20
Calibration Max Change=0.05
Calibration Tolerance=0.2
Calibration Maximum=1.5
Calibration Minimum=0.5
Calibration Optimization Method= 1
WQ AD Non Conservative
WQ ULTIMATE=-1
WQ Max Comp Step=1HOUR
WQ Output Interval=15MIN
WQ Output Selected Increments= 0
WQ Output face flow=0
WQ Output face velocity=0
WQ Output face area=0
WQ Output face dispersion=0
WQ Output cell volume=0
WQ Output cell surface area=0
WQ Output cell continuity=0
WQ Output cumulative cell continuity=0
WQ Output face conc=0
WQ Output face dconc_dx=0
WQ Output face courant=0
WQ Output face peclet=0
WQ Output face adv mass=0
WQ Output face disp mass=0
WQ Output cell mass=0
WQ Output cell source sink temp=0
WQ Output nsm pathways=0
WQ Output nsm derived pathways=0
WQ Output MaxMinRange=-1
WQ Daily Max Min Mean=-1
WQ Daily Range=0
WQ Daily Time=0
WQ Create Restart=0
WQ Fixed Restart=0
WQ System Summary=0
WQ Write To DSS=0
WQ Use Fixed Temperature=0
Sorting and Armoring Iterations= 10
XS Update Threshold= 0.02
Bed Roughness Predictor= 0
Hydraulics Update Threshold= 0.02
Energy Slope Method= 1
Volume Change Method= 1
Sediment Retention Method= 0
XS Weighting Method= 0
Number of US Weighted Cross Sections= 1
Number of DS Weighted Cross Sections= 1
Upstream XS Weight=0
Main XS Weight=1
Downstream XS Weight=0
Number of DS XS's Weighted with US Boundary= 1
Upstream Boundary Weight= 1
Weight of XSs Associated with US Boundary= 0
Number of US XS's Weighted with DS Boundary= 1
Downstream Boundary Weight= 0.5
Weight of XSs Associated with DS Boundary= 0.5
Percentile Method= 0
Sediment Output Level= 3
Mass or Volume Output= 0
Output Increment Type= 1
Profile and TS Output Increment= 1
XS Output Flag= 0
XS Output Increment= 10
Write Gradation File= 0
Read Gradation Hotstart= 0
Write HDF5 File= 1
Write Binary Output= 1
Write DSS Sediment File= 0
SV Curve= 0
Specific Gage Flag= 0

--- BEECHRN.f01 (steady flow) ---

Flow Title=Flows
Program Version=5.07
Number of Profiles= 7
Profile Names=01pct,FW,10pct,04pct,02pct,0_2pct,01plus
River Rch & RM=BEECHRN,Main            ,11840
     281     281     144     194     236     397     415
River Rch & RM=BEECHRN,Main            ,10973
     380     380     198     265     321     535     562
River Rch & RM=BEECHRN,Main            ,7651
     541     541     285     380     457     756     800
River Rch & RM=BEECHRN,Main            ,7316
     639     639     339     450     542     891     945
River Rch & RM=BEECHRN,Main            ,5042
     723     723     386     511     614    1006    1070
River Rch & RM=BEECHRN,Main            ,4021
     815     815     437     577     692    1132    1206
River Rch & RM=BEECHRN,Main            ,1216
     907     907     488     644     771    1257    1342
Boundary for River Rch & Prof#=BEECHRN,Main            , 1
Up Type= 0
Dn Type= 3
Dn Slope=0.01259
Boundary for River Rch & Prof#=BEECHRN,Main            , 2
Up Type= 0
Dn Type= 3
Dn Slope=0.01259
Boundary for River Rch & Prof#=BEECHRN,Main            , 3
Up Type= 0
Dn Type= 3
Dn Slope=0.01259
Boundary for River Rch & Prof#=BEECHRN,Main            , 4
Up Type= 0
Dn Type= 3
Dn Slope=0.01259
Boundary for River Rch & Prof#=BEECHRN,Main            , 5
Up Type= 0
Dn Type= 3
Dn Slope=0.01259
Boundary for River Rch & Prof#=BEECHRN,Main            , 6
Up Type= 0
Dn Type= 3
Dn Slope=0.01259
DSS Import GetInterval= 0
DSS Import GetPeak= 0
DSS Import FillOption= 0

--- BEECHRN.g01 (geometry) ---

Geom Title=Geometry
Program Version=5.07

River Reach=BEECHRN         ,Main
Reach XY= 30
  1988298.875348237743.0987239331988619.08122212237998.593040268
1988923.54667085238102.7138183411989128.40748164238047.592209429
1989220.85545942238104.8837615251989601.93179703237948.633745939
1989708.26885468237986.3941690921989936.13322836237835.786530688
1990423.11256933237814.953239009 1990671.3765085237692.123432174
1991504.41782141237669.1890948411991778.56965958237580.078029573
1992260.20075873237633.0392327761992674.78719985237933.246965691
1993077.14400667238103.1432794331993256.07704777238333.562109932
1993519.61851546238442.9372192771993857.63949293238479.395479694
1994077.43104813238689.2913853381994342.01450846238689.812053591
1994507.11850896238797.1038337651994889.93106353238779.395535856
1995505.52103969239070.1626708361995686.28511387239031.479021192
1995810.76452371239351.2707044331996402.43099126239756.478883505
1996667.01445159240520.5413317531997341.49341762241006.652564272
1997502.37465754241216.2778011711997956.77900001241503.034000009

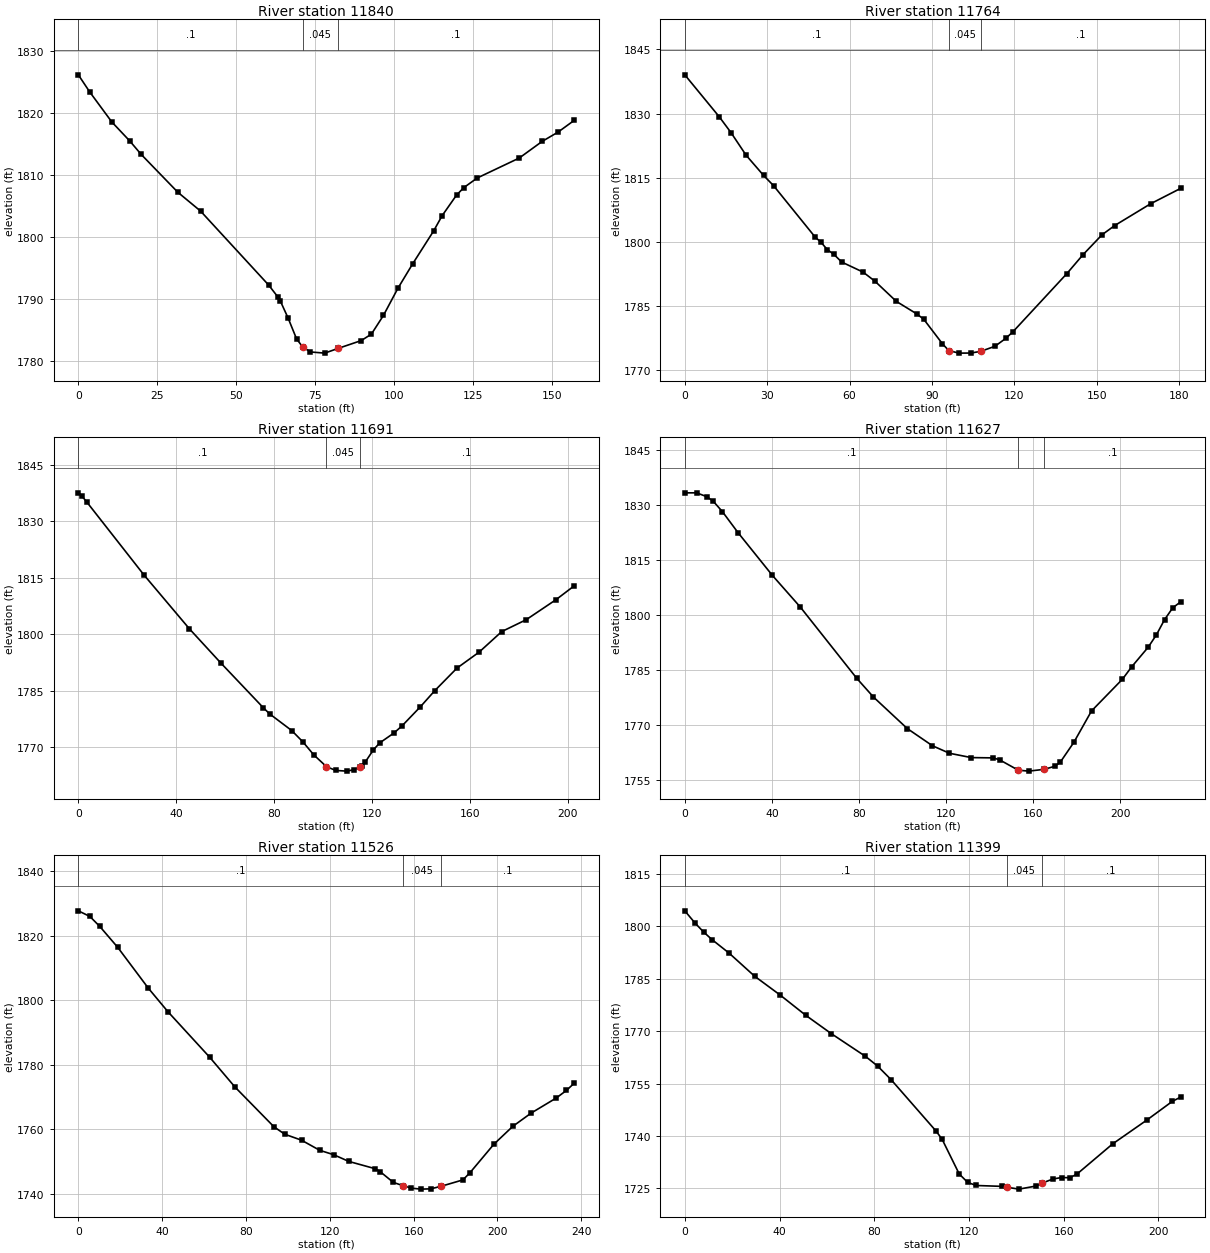
Type RM Length L Ch R = 1 ,11840   ,75.5,75.5,75.5
Node Name=D
XS GIS Cut Line= 2
1988242.68786951237797.877118658 1988359.6742899237693.205058315
#Sta/Elev= 30
       0 1826.22     3.6 1823.46    10.6 1818.61    16.3 1815.53    19.9 1813.37
    31.5 1807.26    38.7 1804.22    60.3 1792.25    63.3 1790.27      64 1789.65
    66.4 1786.97    69.1 1783.58      71  1782.3    73.5 1781.47      78 1781.28
    82.3 1782.05    89.6 1783.31    92.8 1784.35    96.6 1787.36   101.2 1791.76
   105.9 1795.73   112.5 1801.01   115.2 1803.48   119.8 1806.83   122.1 1808.02
   126.3 1809.56   139.6 1812.78   146.9 1815.48   151.9 1816.97     157 1818.86
#Mann= 3 , 0 , 0
       0      .1       0      71    .045       0    82.3      .1       0
Bank Sta=71,82.3
XS Rating Curve= 0 ,0
Exp/Cntr(USF)=0,0
Exp/Cntr=0.3,0.1

Type RM Length L Ch R = 1 ,11764   ,74.1,73.9,72.6
XS GIS Cut Line= 2
1988281.55937367237862.263743784 1988417.1989946237743.144333092
#Sta/Elev= 30
       0 1839.07    12.5 1829.28    16.8 1825.56    22.3 1820.26    28.7  1815.5
    32.3 1813.13    47.4 1801.12    49.6 1799.85    51.9 1798.13    54.3 1797.02
    57.1 1795.24    64.9 1792.88    69.2 1790.76      77 1786.03    84.5 1783.07
      87 1781.83    93.8 1776.09    96.1 1774.51    99.8 1773.91   104.1 1773.93
   107.7 1774.32   112.9 1775.51   116.8 1777.34   119.4 1778.87   139.1 1792.54
   144.9 1796.91   151.9 1801.63   156.5 1803.78   169.6 1808.89   180.5 1812.48
#Mann= 3 , 0 , 0
       0      .1       0    96.1    .045       0   107.7      .1       0
Bank Sta=96.1,107.7
XS Rating Curve= 0 ,0
Exp/Cntr(USF)=0,0
Exp/Cntr=0.3,0.1

Type RM Length L Ch R = 1 ,11691   ,65.4,63.6,60.4
XS GIS Cut Line= 2
1988339.66345483 237921.020719061988478.20000528237773.248398577
#Sta/Elev= 30
       0 1837.61     1.3 1836.88     3.6 1835.04    26.8 1815.78    45.4 1801.43
    58.2 1792.37    75.5 1780.51    78.2  1778.8    87.2 1774.38    91.8 1771.34
    96.2 1767.92   101.4 1764.77   105.2 1763.77   109.7 1763.59   112.7 1763.98
     115 1764.72   115.8 1765.02   117.3 1766.07   120.6 1769.28   123.2 1771.12
   128.9  1773.7   132.2 1775.58   139.8 1780.73   145.7 1785.03   154.7 1790.98
   163.8 1795.26     173  1800.7     183 1803.86   195.2  1809.2   202.6 1812.86
#Mann= 3 , 0 , 0
       0      .1       0   101.4    .045       0     115      .1       0
Bank Sta=101.4,115
XS Rating Curve= 0 ,0
Exp/Cntr(USF)=0,0
Exp/Cntr=0.3,0.1

Type RM Length L Ch R = 1 ,11627   ,98.6,101,102.4
XS GIS Cut Line= 3
1988389.79730307237996.4459821771988463.22045971237879.065540984
1988507.66079135237801.778007688
#Sta/Elev= 30
       0 1833.24     5.4 1833.25    10.1  1832.2    13.1 1830.93    17.3 1828.09
    24.4 1822.42    40.2 1810.74      53 1802.12    78.9  1782.7    86.6 1777.57
   102.1 1768.99   113.7 1764.28   121.5 1762.24   131.5 1761.06   141.6 1760.98
   144.5 1760.45   153.1 1757.62   157.9 1757.37   165.1 1757.87   169.9 1758.71
   172.3 1759.76   178.6 1765.23   186.7 1773.78   200.9 1782.44   205.1 1785.79
   212.7 1791.15   216.5 1794.54   220.2 1798.66     224 1801.91   227.6 1803.52
#Mann= 3 , 0 , 0
       0      .1       0   153.1    .045       0   165.1      .1       0
Bank Sta=153.1,165.1
XS Rating Curve= 0 ,0
Exp/Cntr(USF)=0,0
Exp/Cntr=0.3,0.1

Type RM Length L Ch R = 1 ,11526   ,130,126.7,121.8
XS GIS Cut Line= 2
1988438.17833515238051.8607944881988595.18642567237874.841868909
#Sta/Elev= 30
       0 1827.73     5.5 1825.99    10.2 1822.92    18.8 1816.41    33.4 1803.75
    42.7  1796.5    62.6 1782.41    74.7 1773.15    93.3 1760.82    98.5 1758.48
   106.5 1756.64   115.2  1753.5   121.8 1752.15   129.1 1750.05   141.6 1747.81
     144  1746.9   150.3 1743.56   154.7 1742.59   158.9 1741.77   163.5 1741.47
   168.2 1741.56   172.9 1742.31   183.5 1744.33   186.8 1746.49   198.3 1755.39
   207.3 1760.92   216.1 1765.05     228 1769.69   232.9 1772.05   236.6 1774.29
#Mann= 3 , 0 , 0
       0      .1       0   154.7    .045       0   172.9      .1       0
Bank Sta=154.7,172.9
XS Rating Curve= 0 ,0
Exp/Cntr(USF)=0,0
Exp/Cntr=0.3,0.1

Type RM Length L Ch R = 1 ,11399   ,138.2,136.6,133.4
XS GIS Cut Line= 2
1988587.48995064238130.3648397451988673.69047092237939.492259121
#Sta/Elev= 30
       0 1804.42     4.3 1800.94     7.9 1798.39    11.5 1796.18    18.7 1792.32
    29.5  1785.7    40.3  1780.3    51.1 1774.51    61.9 1769.26    76.3 1762.77
    81.4 1760.01    87.1 1756.12   106.2 1741.32   108.7    1739   115.9  1729.1
   119.5 1726.68   123.1 1725.81   133.9 1725.56   135.9 1725.33   141.1 1724.77
   148.3 1725.65   150.8 1726.48   155.5 1727.67   159.1 1728.09   162.7 1728.03
   165.7 1729.12   180.7 1737.72   195.1 1744.52   205.9 1749.89   209.4 1751.11
#Mann= 3 , 0 , 0
       0      .1       0   135.9    .045       0   150.8      .1       0
Bank Sta=135.9,150.8
XS Rating Curve= 0 ,0
Exp/Cntr(USF)=0,0
Exp/Cntr=0.3,0.1

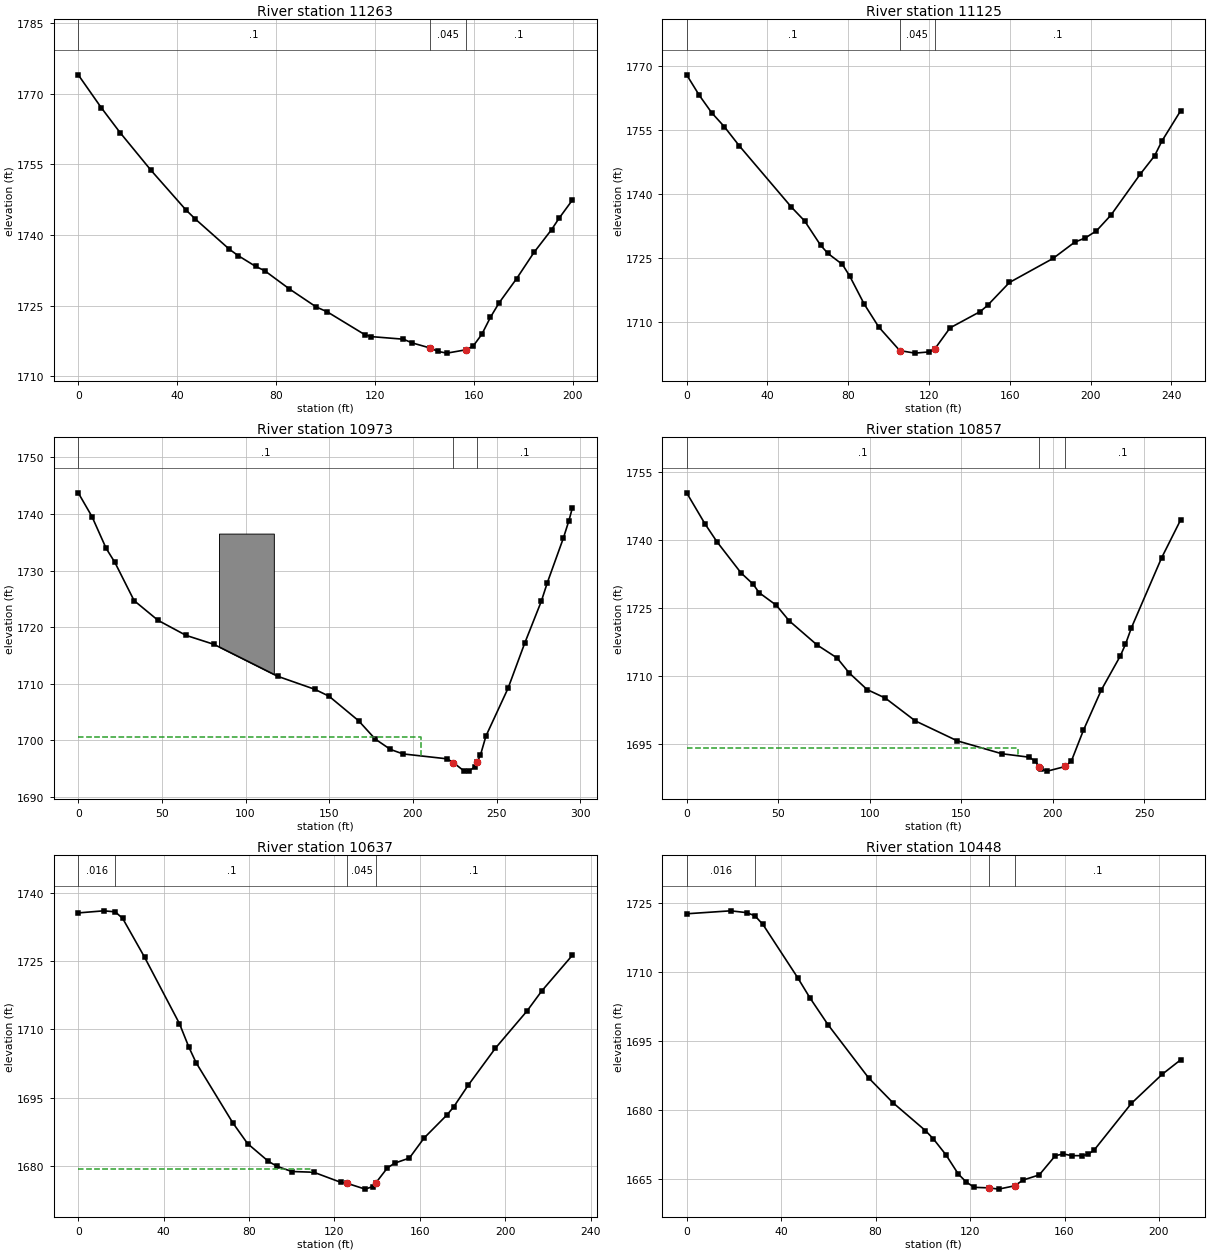
Type RM Length L Ch R = 1 ,11263   ,135.8,137.4,136.3
XS GIS Cut Line= 2
1988722.94791109  238147.29708481988795.29477632237961.042389191
#Sta/Elev= 30
       0 1774.06     9.3 1767.08    16.9 1761.79    29.4 1753.78    43.5 1745.37
    47.4 1743.38    61.1 1736.99    64.6 1735.65    71.7 1733.35    75.4 1732.42
    85.4 1728.54    96.3 1724.69   100.6 1723.71   115.8 1718.85   118.3 1718.42
   131.5 1717.86     135 1717.08   142.1 1716.02   145.6 1715.25   149.1  1714.9
   156.9 1715.62   159.7 1716.39   163.2 1718.89   166.7 1722.52   170.2 1725.59
   177.3 1730.75   184.3  1736.3   191.4 1741.14   194.4 1743.53   199.8 1747.41
#Mann= 3 , 0 , 0
       0      .1       0   142.1    .045       0   156.9      .1       0
Bank Sta=142.1,156.9
XS Rating Curve= 0 ,0
Exp/Cntr(USF)=0,0
Exp/Cntr=0.3,0.1

Type RM Length L Ch R = 1 ,11125   ,158,152.2,143.5
XS GIS Cut Line= 2
1988835.31644645238193.4759349511988935.37062178237970.278159221
#Sta/Elev= 30
       0 1767.83     6.2 1763.08    12.4 1758.97    18.6 1755.74    26.1 1751.22
    51.9 1736.91    58.4  1733.7    66.3 1728.04    69.9 1726.13    77.1 1723.55
    80.7 1720.85    87.9 1714.28    95.1 1708.93   105.5 1703.42     113 1702.83
   120.2 1703.12   122.9 1703.85   130.4 1708.73   145.4 1712.55     149    1714
   159.8 1719.33   181.4 1724.95   192.1 1728.74   197.4 1729.74   202.9  1731.4
   210.1 1735.09   224.5 1744.59   231.7 1748.94   235.3 1752.37   244.6 1759.46
#Mann= 3 , 0 , 0
       0      .1       0   105.5    .045       0   122.9      .1       0
Bank Sta=105.5,122.9
XS Rating Curve= 0 ,0
Exp/Cntr(USF)=0,0
Exp/Cntr=0.3,0.1

Type RM Length L Ch R = 1 ,10973   ,113.9,115.5,117.1
XS GIS Cut Line= 4
1988949.32282249238263.1736426991989023.20898273238143.108632306
 1989032.2499236238132.1822125281989014.41730033237993.133662222
#Sta/Elev= 30
       0 1743.73     8.2 1739.54    16.7 1733.91    21.9 1731.44    33.4 1724.69
    47.7 1721.21    64.4 1718.56    81.1 1716.97   119.2 1711.33   141.4 1709.03
   149.9 1707.81   167.6 1703.47   177.5 1700.25   186.6 1698.41   194.1 1697.62
   220.5 1696.75   224.21696.086   230.4 1694.65   233.5 1694.58   237.1 1695.35
   238.61696.277   240.4 1697.41   243.7 1700.78   256.9 1709.21   266.8 1717.13
   276.8 1724.59   280.4 1727.88     290 1735.76   293.3 1738.84   295.3 1741.01
#Mann= 3 , 0 , 0
       0      .1       0   224.2    .045       0   238.6      .1       0
#XS Ineff= 2 , 0
             205 1700.55
Permanent Ineff=
       F       F
#Block Obstruct= 1 ,-1
   84.11  116.91 1736.53
Bank Sta=224.2,238.6
XS Rating Curve= 0 ,0
Exp/Cntr(USF)=0,0
Exp/Cntr=0.3,0.1

Type RM Length L Ch R = 1 ,10857   ,221.1,220.3,213.4
XS GIS Cut Line= 2
1989129.47382155238247.9593766731989138.97564257237978.107659741
#Sta/Elev= 30
       0 1750.35      10 1743.53    16.6 1739.56    29.7 1732.74    36.3 1730.27
    39.6 1728.39      49 1725.62      56 1722.21    71.2 1716.91    82.2 1714.03
    88.8 1710.75    98.6 1707.08   108.5 1705.22   124.9  1700.2   147.9  1695.8
   172.3 1692.96   187.3  1692.2   190.6 1691.27   192.7 1690.14   193.8 1689.57
   197.1 1689.14     207 1690.17   210.3 1691.41   216.8  1698.1   226.6 1706.98
     237 1714.48   239.8 1717.03   243.1 1720.71   259.5    1736     270 1744.43
#Mann= 3 , 0 , 0
       0      .1       0   192.7    .045       0     207      .1       0
#XS Ineff= 2 , 0
          180.85 1694.27
Permanent Ineff=
       F       F
Bank Sta=192.7,207
XS Rating Curve= 0 ,0
Exp/Cntr(USF)=0,0
Exp/Cntr=0.3,0.1

Type RM Length L Ch R = 1 ,10637   ,189.3,189.6,189.2
XS GIS Cut Line= 2
  1989357.517526238175.7455369311989287.20405046237955.303289296
#Sta/Elev= 30
       0 1735.59    11.9 1736.05    17.3 1735.83    20.8 1734.39    31.1 1725.84
    47.4 1711.29    51.8 1706.14    55.2 1702.71    72.4  1689.5    79.3 1684.95
    89.1 1681.04    93.1 1679.96     100 1678.82   110.3 1678.66   123.1 1676.42
   126.1  1676.2   134.4 1674.95   137.9 1675.51  139.481676.378   144.8 1679.61
   148.2 1680.65   155.1 1681.77     162 1686.18   172.7 1691.24   175.8 1692.97
   182.6 1697.73   195.4  1705.9   210.2 1714.06   217.1 1718.46   231.4 1726.27
#Mann= 4 ,-1 , 0
       0    .016       0    17.3      .1       0   126.1    .045       0
  139.48      .1       0
#XS Ineff= 2 , 0
          109.01 1679.32
Permanent Ineff=
       F       F
Bank Sta=126.1,139.48
XS Rating Curve= 0 ,0
Exp/Cntr(USF)=0,0
Exp/Cntr=0.3,0.1

Type RM Length L Ch R = 1 ,10448   ,229.1,231.3,230
XS GIS Cut Line= 2
1989536.15176115238124.4357034291989473.43974243237924.897462036
#Sta/Elev= 30
       0 1722.58    18.6 1723.22    25.4 1722.83    28.9 1722.14    32.3 1720.26
      47 1708.73    52.2 1704.35    59.8 1698.57      77 1687.03    87.3 1681.64
   101.1 1675.58   104.5 1673.76   109.8 1670.32     115 1666.18   118.3 1664.47
   121.7 1663.28   128.1 1663.16   132.1 1662.89   138.9 1663.61   142.4 1664.85
   149.3 1665.97   156.1 1670.14   159.5 1670.52     163 1670.15   167.3 1670.14
   169.9 1670.41   172.6 1671.39   188.3 1681.47   201.3 1687.76   209.2 1690.93
#Mann= 4 ,-1 , 0
       0    .016       0    28.9       0       0   128.1    .045       0
   138.9      .1       0
Bank Sta=128.1,138.9
XS Rating Curve= 0 ,0
Exp/Cntr(USF)=0,0
Exp/Cntr=0.3,0.1

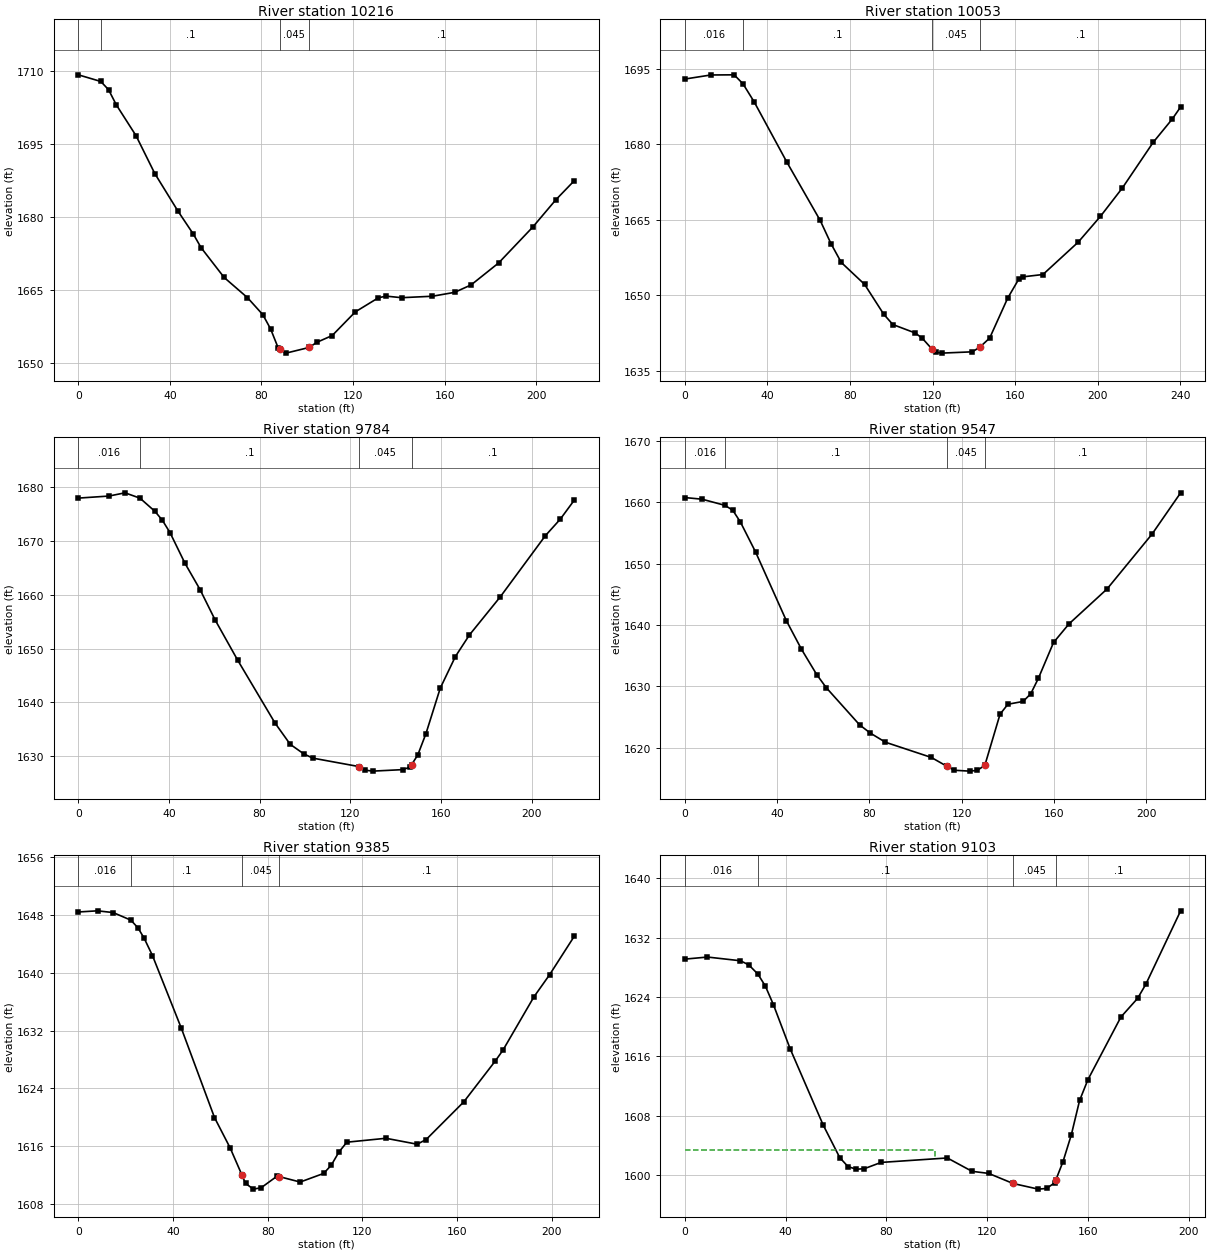
Type RM Length L Ch R = 1 ,10216   ,165.6,163.4,156.1
XS GIS Cut Line= 2
1989722.38745312238076.9265983361989672.97798382 237865.98617172
#Sta/Elev= 30
       0 1709.16     9.8  1707.8    13.2 1706.11    16.6 1702.99    25.2 1696.67
    33.4  1688.9    43.5  1681.2    50.3 1676.42    53.6 1673.69    63.7 1667.56
    73.9 1663.41    80.6 1659.92      84 1656.99    87.3  1653.1      88 1652.86
    90.7 1652.03   100.8 1653.19   104.2 1654.25   110.9 1655.64     121  1660.5
   131.1  1663.4   134.5 1663.73   141.2 1663.41   154.7 1663.71   164.4 1664.51
   171.6 1666.04   183.6 1670.54   198.5  1677.9   208.6 1683.51   216.6  1687.4
#Mann= 4 ,-1 , 0
       0    .016       0     9.8      .1       0      88    .045       0
   100.8      .1       0
Bank Sta=88,100.8
XS Rating Curve= 0 ,0
Exp/Cntr(USF)=0,0
Exp/Cntr=0.3,0.1

Type RM Length L Ch R = 1 ,10053   ,263.6,268.9,279.8
XS GIS Cut Line= 2
 1989914.3242377237997.1113017781989760.39473719237812.775974015
#Sta/Elev= 30
       0 1692.96    12.6 1693.77    23.9  1693.8    28.2 1692.01    33.6 1688.43
    49.5 1676.41    65.6 1664.86    70.8 1660.27    75.8 1656.52    87.1 1652.16
    96.4 1646.21   100.8 1644.18   111.7 1642.49   115.1 1641.43   119.7 1639.33
   121.9 1638.66   124.4  1638.5   139.3 1638.76     143 1639.71   147.7  1641.5
   156.4 1649.41   161.7 1653.14     164 1653.67   173.5 1654.12   190.6 1660.56
   201.3 1665.65     212 1671.33   226.9 1680.38   236.2 1685.04   240.2 1687.42
#Mann= 4 ,-1 , 0
       0    .016       0    28.2      .1       0   119.7    .045       0
     143      .1       0
Bank Sta=119.7,143
XS Rating Curve= 0 ,0
Exp/Cntr(USF)=0,0
Exp/Cntr=0.3,0.1

Type RM Length L Ch R = 1 ,9784    ,235.3,236.7,234.6
XS GIS Cut Line= 2
1990096.75920126237940.100375666  1990066.353374237723.458856439
#Sta/Elev= 30
       0 1677.94    13.5 1678.32    20.6 1678.92    27.2 1677.93    33.8 1675.48
    37.1 1673.82    40.5 1671.49    47.1  1665.8    53.7 1660.96    60.3 1655.36
    70.3 1647.85    86.8 1636.16    93.5 1632.21    99.4 1630.46   103.4 1629.65
   123.9 1628.07   126.6 1627.41   129.9 1627.23   143.2 1627.51   146.5 1627.99
   147.1 1628.45   149.8 1630.24   153.4  1634.2   159.7 1642.63   166.4 1648.52
   172.6 1652.53   186.2  1659.6   206.1 1670.96   212.7 1674.04   218.8 1677.53
#Mann= 4 ,-1 , 0
       0    .016       0    27.2      .1       0   123.9    .045       0
   147.1      .1       0
Bank Sta=123.9,147.1
XS Rating Curve= 0 ,0
Exp/Cntr(USF)=0,0
Exp/Cntr=0.3,0.1

Type RM Length L Ch R = 1 ,9547    ,162.7,162.4,164.3
XS GIS Cut Line= 2
1990311.50035628237917.2960052211990281.09452902237704.455214401
#Sta/Elev= 30
       0 1660.79     7.5 1660.52    17.4 1659.52    20.8 1658.72    24.1 1656.81
    30.7 1651.91      44 1640.75    50.6 1636.06    57.2 1631.94    61.3 1629.82
    75.8 1623.74    80.4 1622.41      87 1620.91   106.9 1618.43   113.6    1617
   113.6 1616.99   116.9 1616.34   123.5  1616.2   126.8 1616.32   130.1 1617.14
   136.7 1625.48   140.1  1627.1   146.7 1627.56     150  1628.8   153.3 1631.31
   159.9 1637.17   166.6  1640.2   183.1 1645.89   202.6 1654.83     215 1661.56
#Mann= 4 ,-1 , 0
       0    .016       0    17.4      .1       0   113.6    .045       0
   130.1      .1       0
Bank Sta=113.6,130.1
XS Rating Curve= 0 ,0
Exp/Cntr(USF)=0,0
Exp/Cntr=0.3,0.1

Type RM Length L Ch R = 1 ,9385    ,282.5,281.3,284.3
Node Name=C
XS GIS Cut Line= 2
1990458.96861849237888.4104693241990441.86534066237679.750479753
#Sta/Elev= 30
       0 1648.39     8.1 1648.55    14.7 1648.31    22.2 1647.26    25.2 1646.19
    27.8 1644.76    31.3 1642.37    43.5 1632.32    57.5 1619.97    64.1 1615.78
   69.151611.982    70.6 1610.87    73.9 1610.07    77.2 1610.26    83.8 1611.83
    84.7 1611.81    93.7 1611.05   103.6 1612.24   106.8 1613.37   110.1 1615.22
   113.4 1616.56   129.9  1617.1   143.1 1616.28   146.9 1616.93   162.8 1622.14
     176 1627.75   179.3 1629.27   192.4 1636.65     199  1639.7   209.4 1645.01
#Mann= 4 ,-1 , 0
       0    .016       0    22.2      .1       0   69.15    .045       0
    84.7      .1       0
Bank Sta=69.15,84.7
XS Rating Curve= 0 ,0
Exp/Cntr(USF)=0,0
Exp/Cntr=0.3,0.1

Type RM Length L Ch R = 1 ,9103    ,259.3,259,258.3
XS GIS Cut Line= 2
1990706.96614708237830.2593246891990700.12483595237633.571629602
#Sta/Elev= 30
       0 1629.12       9  1629.4    22.1  1628.9    25.4 1628.34      29 1627.11
      32 1625.47    35.2 1622.96    41.8 1617.05    54.9 1606.78    61.5 1602.37
    64.8 1601.15    68.1  1600.8    71.3 1600.88    77.9 1601.72   104.2 1602.32
     114 1600.52   120.6 1600.24   130.3 1598.88   140.3 1598.12   143.6 1598.21
   146.9    1599   147.3 1599.38   150.1 1601.81   153.4 1605.42   156.7 1610.07
     160 1612.87   173.1 1621.32   179.7 1623.82     183 1625.74   196.8 1635.63
#Mann= 4 ,-1 , 0
       0    .016       0      29      .1       0   130.3    .045       0
   147.3      .1       0
#XS Ineff= 2 , 0
           99.38 1603.44
Permanent Ineff=
       F       F
Bank Sta=130.3,147.3
XS Rating Curve= 0 ,0
Exp/Cntr(USF)=0,0
Exp/Cntr=0.3,0.1

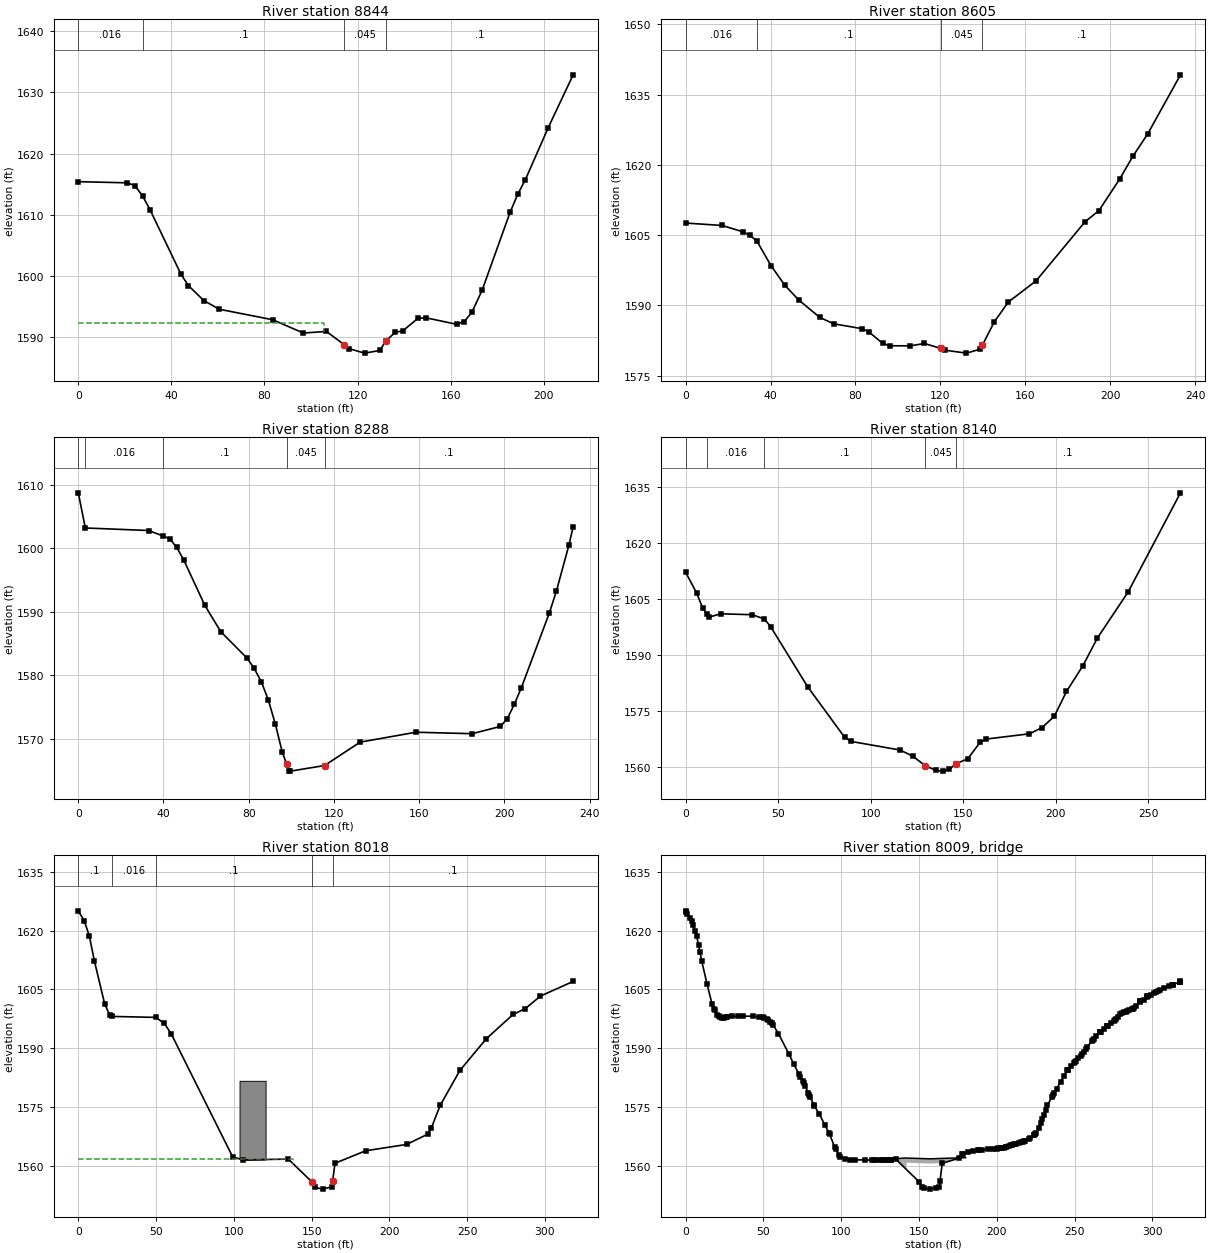
Type RM Length L Ch R = 1 ,8844    ,238.9,238.9,239
XS GIS Cut Line= 2
1990968.64629794237802.8940801551990953.25334789237590.813435017
#Sta/Elev= 30
       0 1615.41      21 1615.22    24.3 1614.77    27.6 1613.09    30.9 1610.77
    44.1 1600.31    47.3 1598.45    53.9 1596.01    60.5 1594.59    83.5 1592.87
    96.7  1590.7   106.6 1590.96   114.3 1588.78   116.4 1588.14     123 1587.42
   129.6 1587.86     132 1589.37   136.2 1590.83   139.4 1591.05     146 1593.12
   149.3 1593.19   162.5 1592.13   165.8 1592.57   169.1 1594.09   173.5 1597.69
   185.5  1610.4   188.8 1613.36   192.1 1615.76   201.9 1624.23   212.6 1632.85
#Mann= 4 ,-1 , 0
       0    .016       0    27.6      .1       0   114.3    .045       0
     132      .1       0
#XS Ineff= 2 , 0
          105.35 1592.36
Permanent Ineff=
       F       F
Bank Sta=114.3,132
XS Rating Curve= 0 ,0
Exp/Cntr(USF)=0,0
Exp/Cntr=0.3,0.1

Type RM Length L Ch R = 1 ,8605    ,316.6,317.1,315.3
XS GIS Cut Line= 2
1991204.67153204237789.2114578891991189.27858199 237556.60687935
#Sta/Elev= 30
       0 1607.59    17.2 1607.07      27 1605.72    30.3 1604.97    33.6 1603.72
    40.2  1598.5    46.8 1594.27    53.3 1591.16    63.2 1587.44    69.8 1586.07
    82.9 1585.06    86.2  1584.4    92.8  1581.9    96.1 1581.39   105.9 1581.38
   112.5 1581.88   120.1 1580.83   122.4 1580.43   132.3 1579.82   138.8 1580.67
   139.8 1581.51   145.4 1586.51     152 1590.72   165.1 1595.26   188.1 1607.84
   194.7 1610.25   204.6 1617.09   210.7 1621.86   217.7 1626.65   233.1 1639.23
#Mann= 4 ,-1 , 0
       0    .016       0    33.6      .1       0   120.1    .045       0
   139.8      .1       0
Bank Sta=120.1,139.8
XS Rating Curve= 0 ,0
Exp/Cntr(USF)=0,0
Exp/Cntr=0.3,0.1

Type RM Length L Ch R = 1 ,8288    ,148.7,148.5,146.9
XS GIS Cut Line= 2
 1991517.6615164237772.1081800551991492.00659965  237541.2139293
#Sta/Elev= 30
       0 1608.73     3.3  1603.2      33  1602.8    39.6 1601.97    42.9  1601.5
    46.2 1600.16    49.5 1598.17    59.4 1591.02    66.9 1586.88    79.3 1582.69
    82.6 1581.09    85.9 1579.02    89.2 1576.15    92.5 1572.34    95.8 1567.88
   97.841566.029    99.1 1564.95    99.6 1564.94   115.6 1565.82   132.3  1569.5
   158.5 1571.06   184.9 1570.83   198.1 1571.97   201.4 1573.18   204.7 1575.47
     208 1578.07   221.2 1589.89   224.4 1593.23   230.3 1600.48   232.3 1603.39
#Mann= 5 ,-1 , 0
       0      .1       0     3.3    .016       0    39.6      .1       0
   97.84    .045       0   115.6      .1       0
Bank Sta=97.84,115.6
XS Rating Curve= 0 ,0
Exp/Cntr(USF)=0,0
Exp/Cntr=0.3,0.1

Type RM Length L Ch R = 1 ,8140    ,120.9,121.6,122.9
XS GIS Cut Line= 2
1991669.88068912237755.0049022211991623.70183897237491.614423582
#Sta/Elev= 30
       0 1612.24       6 1606.62     9.3 1602.52    11.7  1600.9    12.6 1600.19
      19 1601.09      36 1600.84    42.6 1599.68      46 1597.58    65.9 1581.54
    85.9 1567.95    89.3 1566.85   115.9 1564.53   122.6 1562.91   129.5 1560.35
   135.2 1559.05   139.2 1558.87   142.5 1559.34   145.9 1560.81   152.5  1562.2
   159.2 1566.65   162.5 1567.48   185.8 1568.89   192.5 1570.53   199.2 1573.56
   205.8 1580.24   214.6  1587.1   222.5 1594.58   239.1 1606.94   267.4 1633.55
#Mann= 5 ,-1 , 0
       0      .1       0    11.7    .016       0    42.6      .1       0
   129.5    .045       0   145.9      .1       0
Bank Sta=129.5,145.9
XS Rating Curve= 0 ,0
Exp/Cntr(USF)=0,0
Exp/Cntr=0.5,0.3

Type RM Length L Ch R = 1 ,8018    ,30.9,31.1,31
BEGIN DESCRIPTION:
Channel burned from survey ID: 54089BER112BU
END DESCRIPTION:
XS GIS Cut Line= 3
1991771.23127813237739.7796838471991755.89252861237515.833940826
1991696.07140548237443.741818072
#Sta/Elev= 30
       0 1625.02     3.8  1622.5     7.1 1618.64    10.4 1612.16      17 1601.25
    20.2  1598.5    21.4 1598.13    49.8 1597.88    55.3 1596.36    59.7 1593.72
    99.2 1562.39   105.7 1561.59     135 1561.79     1501556.047     1521554.624
     1571554.143     1631554.728  163.55 1556.33     1651560.726   184.7 1563.91
     211 1565.52   224.5 1568.11   226.9 1569.66   232.6 1575.45   245.3 1584.37
   262.4 1592.49   279.5 1598.63   287.4 1600.14   297.1 1603.31   318.1 1607.04
#Mann= 5 ,-1 , 0
       0      .1       0    21.4    .016       0    49.8      .1       0
     150    .045       0  163.55      .1       0
#XS Ineff= 2 , 0
             138  1561.9     179          1561.9
Permanent Ineff=
       F       F
#Block Obstruct= 1 ,-1
  103.65  120.41 1581.73
Bank Sta=150,163.55
XS Rating Curve= 0 ,0
Exp/Cntr(USF)=0,0
Exp/Cntr=0.5,0.3

Type RM Length L Ch R = 3 ,8009    ,,,
BEGIN DESCRIPTION:
Private Dr
Survey ID: BER110
END DESCRIPTION:
Bridge Culvert--1,0,-1,-1, 0
Deck Dist Width WeirC Skew NumUp NumDn MinLoCord MaxHiCord MaxSubmerge Is_Ogee
11,8,2.6,0, 10, 10, , , 0.98, 0, 0,0,,
     130     134     141     142     142     157     170     170     171     180
1561.0591561.8751562.061 1562.06 1562.061561.861 1562.04 1562.041562.0411562.151
                                 1560.86 1560.66 1560.84
     130     134     141     142     142     157     170     170     171     180
1561.0591561.8751562.061 1562.06 1562.061561.861 1562.04 1562.041562.0411562.151
                                 1560.86 1560.66 1560.84
BR Coef=-1 , 1 , 0 ,, 0 ,,,0.8,0,1.2,0,
WSPro=,,,, 1 ,,,, 0 ,,,, 0 ,,,,-1 ,-1 ,-1 , 0 , 0 , 0 , 0 , 0
BR U #Sta/Elev= 183
       0 1625.02      .5 1624.72     1.2 1624.19     2.9 1623.13     3.8  1622.5
     4.8  1621.3       6 1619.97     7.1 1618.64     8.3 1616.25     9.1 1614.64
    10.4 1612.16    13.7 1606.48      17 1601.25    18.3 1600.06    18.9 1599.64
    20.2  1598.5    21.4 1598.13    22.4 1597.98    23.5 1597.65    24.5 1597.79
      26 1597.97    26.8 1598.09    30.1 1598.13    33.4 1598.14    36.7 1598.21
    43.3 1598.17    47.1 1597.99    49.8 1597.88    50.7  1597.7    52.2 1597.42
    53.1 1597.21    54.2 1596.76    55.3 1596.36    56.4 1595.86    59.7 1593.72
    66.3 1588.62    69.6  1585.9    72.9 1583.42    73.7  1582.8    75.4 1581.67
    76.1 1581.13    76.8  1580.5    78.9 1578.55    79.4 1578.05    79.9 1577.72
    82.4 1575.58    82.7 1575.37      86  1573.2    89.5 1570.47    92.2 1568.41
    92.6  1568.1    95.9 1564.75    96.6 1564.32    98.4 1562.87    99.2 1562.39
   102.5 1561.81   105.7 1561.59     109 1561.61   115.6 1561.57   119.9 1561.54
   121.3 1561.51   122.2 1561.51   125.5 1561.46   126.1 1561.46   128.8 1561.48
   129.1 1561.48   131.9 1561.47   132.2 1561.47     135 1561.79     1501556.047
     1521554.624     153 1554.44     1571554.143     1611554.445     1631554.728
  163.55 1556.33     1651560.726     176 1562.05   177.8  1563.1   178.1 1563.16
   181.3 1563.49   184.7 1563.91     188 1564.07   188.4 1564.09   190.7 1564.14
   194.5  1564.3   197.8 1564.35   199.9 1564.47   201.1 1564.53   202.5 1564.61
     203 1564.63   204.4 1564.71     206 1564.92   206.1 1564.93   207.7 1565.15
   209.2 1565.31   209.5 1565.36     211 1565.52   212.2 1565.68   214.3 1565.97
   215.3  1566.1   216.6 1566.25   217.6 1566.37   218.4 1566.52   220.8 1566.99
   221.5 1567.15   223.7 1567.86   224.1 1567.98   224.5 1568.11   224.5 1568.14
   225.1 1568.49   226.9 1569.66   228.3 1570.98   229.2  1571.9   230.3 1573.04
   231.5 1574.38   232.6 1575.45   235.4  1577.6   236.2 1578.12   236.8 1578.58
   238.5  1579.7   241.1 1581.55   243.2 1582.88   245.3 1584.37   245.5 1584.45
   245.7 1584.56   247.8 1585.57   249.6 1586.37   250.2 1586.59   250.8 1586.87
   252.5 1587.51   253.9 1588.14   254.8 1588.55   255.9  1589.1   257.1 1589.72
   258.1 1590.29   261.1 1591.82   261.8 1592.18   262.4 1592.49   264.1 1593.14
   266.2 1594.07   266.5 1594.18   266.7 1594.26   268.8 1594.93   270.9 1595.61
   271.1 1595.66   271.4 1595.73   273.5  1596.4   275.2 1597.02   275.8  1597.2
   276.5 1597.44   278.1 1598.03   279.5 1598.63   280.4  1598.9   281.6 1599.16
   282.8 1599.35   283.7 1599.54   285.1 1599.72   286.8    1600   287.4 1600.14
     288  1600.3   289.8 1600.81   291.9  1601.9   292.1 1601.96   292.2 1602.01
   294.4  1602.4   296.5 1603.13   296.8 1603.21   297.1 1603.31   299.1 1603.59
   300.8    1604   302.2 1604.28   303.7 1604.51     305 1604.83   307.3 1605.31
   310.7 1605.75   312.5 1606.04   313.1 1606.16   313.6 1606.25   317.6 1606.94
   317.7 1606.97   317.8 1606.98   318.1 1607.04
BR U #Mann= 5
       0      .1    21.4    .016    49.8      .1     150     .04  163.55      .1
BR D #Sta/Elev= 172
       0  1627.6     4.2 1625.19     7.3 1623.41    10.4 1620.61    10.6  1620.4
    10.8 1619.95    13.5 1615.73    14.4 1614.01    16.5  1609.6    17.9 1607.03
    19.6 1603.52    20.5 1601.93    21.4 1600.53    22.7 1598.57    23.7 1597.06
      25 1596.75    25.8 1596.49      27 1596.18    30.3 1596.65    33.6 1596.76
    43.5    1597    46.8 1597.01    49.7 1596.99    53.2 1596.94    56.6 1596.78
    59.6  1596.3    59.9 1596.24    63.2 1595.26    65.8  1593.8    66.5 1593.37
    67.3 1592.81    68.9 1591.83    69.8  1591.2    70.8 1590.37    71.9 1589.56
    73.1 1588.67    76.4 1585.61    79.6 1582.16    82.9 1579.37    84.2 1578.33
      85 1577.82    86.2 1576.83    87.3 1576.06    88.5 1575.25    89.5 1574.54
    90.4 1573.78      92 1572.53    93.5 1571.29    95.6  1569.6    96.1 1569.15
    99.4 1566.17   102.7 1562.84     106 1561.84   112.5 1561.83   115.8 1561.77
   116.7 1561.76   119.1 1561.74   122.4 1561.69     129 1561.51     1301561.124
     1351561.994     1461555.642     1501554.133     1531553.884     1601554.437
     1621554.557  163.46 1555.83     1651557.662   168.4 1561.24   169.7 1561.59
   170.4 1561.82   171.7 1562.18   173.2 1562.23     175  1562.3   176.6 1562.35
   178.3 1562.42   179.7  1562.5   180.3 1562.52   181.6 1562.59   182.7 1562.68
   184.9 1562.84   188.9 1562.94   190.9 1562.97   194.4  1563.1     195 1563.12
   197.9 1563.19     198 1563.19   198.1 1563.19   199.4 1563.24   201.2 1563.31
   201.3 1563.31   204.6  1563.5     205 1563.51   207.4 1563.58   207.9  1563.6
   208.5 1563.63   210.4 1563.68   211.2 1563.71   212.1 1563.75   213.5  1563.8
   215.6 1563.92   217.8 1564.09   221.1 1564.23   224.5 1564.48   226.9 1564.61
   227.8 1564.62   230.2 1564.67   232.1 1564.79   232.5 1564.82   232.8 1564.86
   234.8 1565.11   236.6 1565.31   237.1 1565.37   241.8 1565.63   242.3 1565.68
   244.1 1565.82   247.5 1566.07   248.8  1566.2   252.6 1566.47   253.5 1566.61
   254.1 1566.66   257.7 1567.18   258.1 1567.29   258.4 1567.36   260.4  1567.9
   261.6 1568.18   262.7 1568.43   262.8 1568.45   262.9 1568.49   266.9 1570.98
   267.4  1571.2     268 1571.42   269.8  1572.3   271.2 1572.77   272.1 1573.06
   273.2 1573.34   274.4  1573.8   275.5 1574.11   276.8 1574.54   278.3 1574.96
   279.1 1575.24   279.7 1575.49   281.4  1576.2   283.4 1576.98   283.7  1577.1
     284 1577.18   286.1  1577.9   286.7 1578.15   288.3 1578.79   288.4 1578.83
   290.7 1578.79   292.5  1578.7   293.1 1578.77   293.7 1578.76   295.4 1578.77
   296.8 1578.84   298.9 1579.49   300.1 1579.83     301 1580.09   302.4 1580.49
     304 1581.04   304.7 1581.21   305.3  1581.3     307 1581.49   309.1 1581.63
   309.4 1581.64   309.6 1581.63   311.7 1581.64   311.7 1581.65   313.8 1581.89
     314  1581.9   318.1  1582.6
BR D #Mann= 5
       0      .1    23.7    .016    59.6      .1     146     .04  163.46      .1
BC Design=,, 0 ,, 0 ,,,,,,
BC Use User HTab Curves=0
BC User HTab FreeFlow(D)= 0