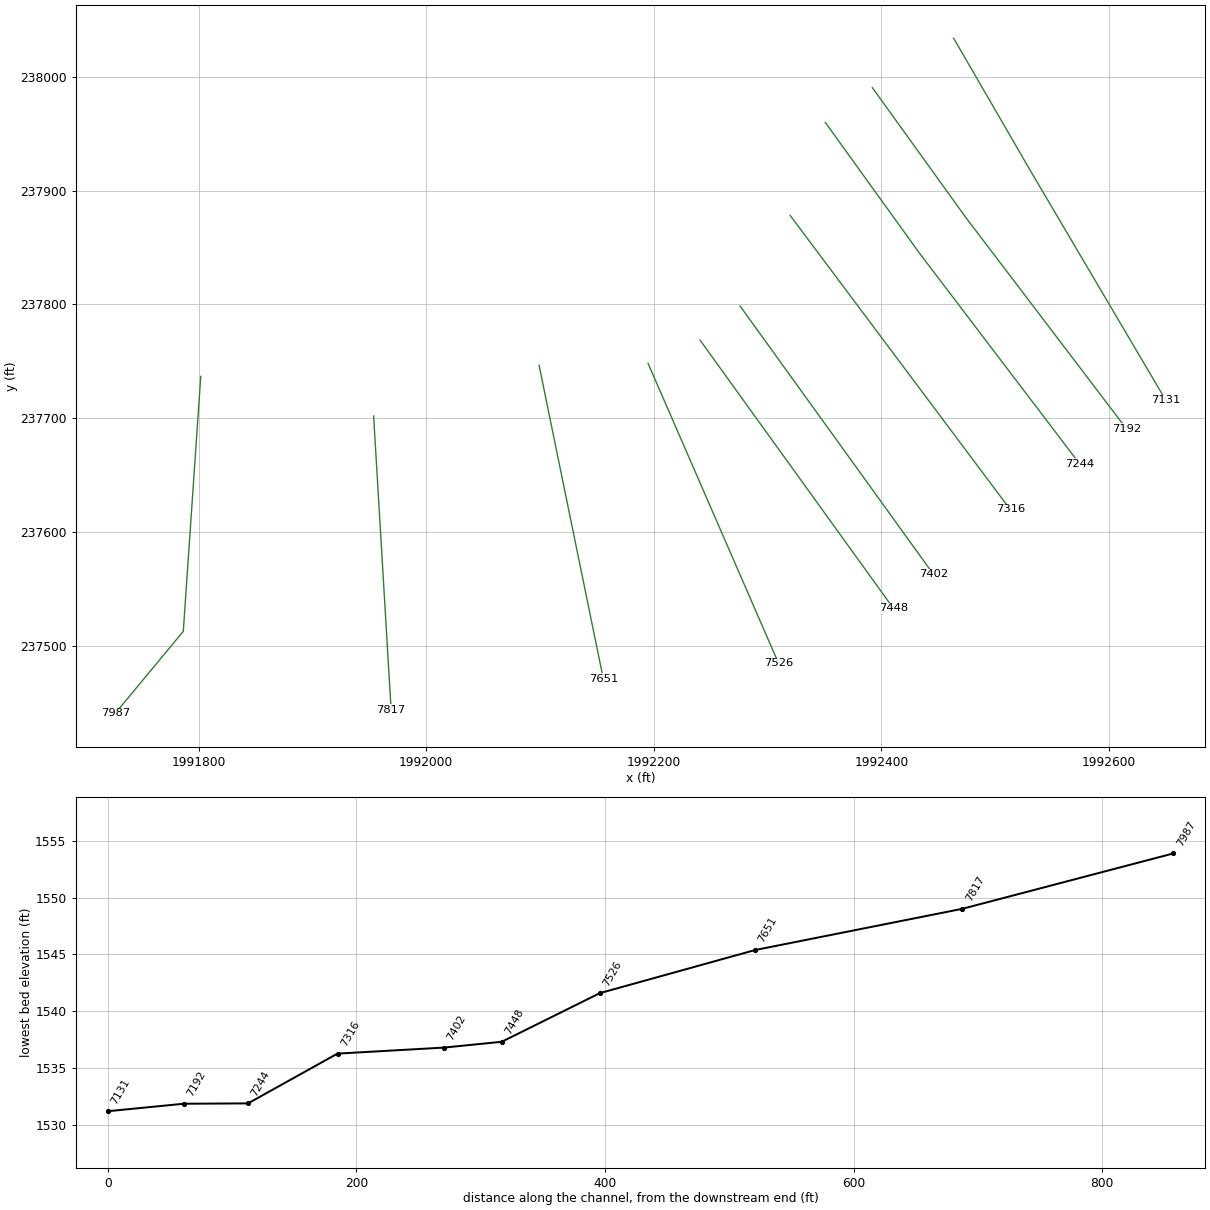
HEC-RAS study BEECHRN.prj: BEECHRN

--- BEECHRN.g01 (geometry) --- (continued)

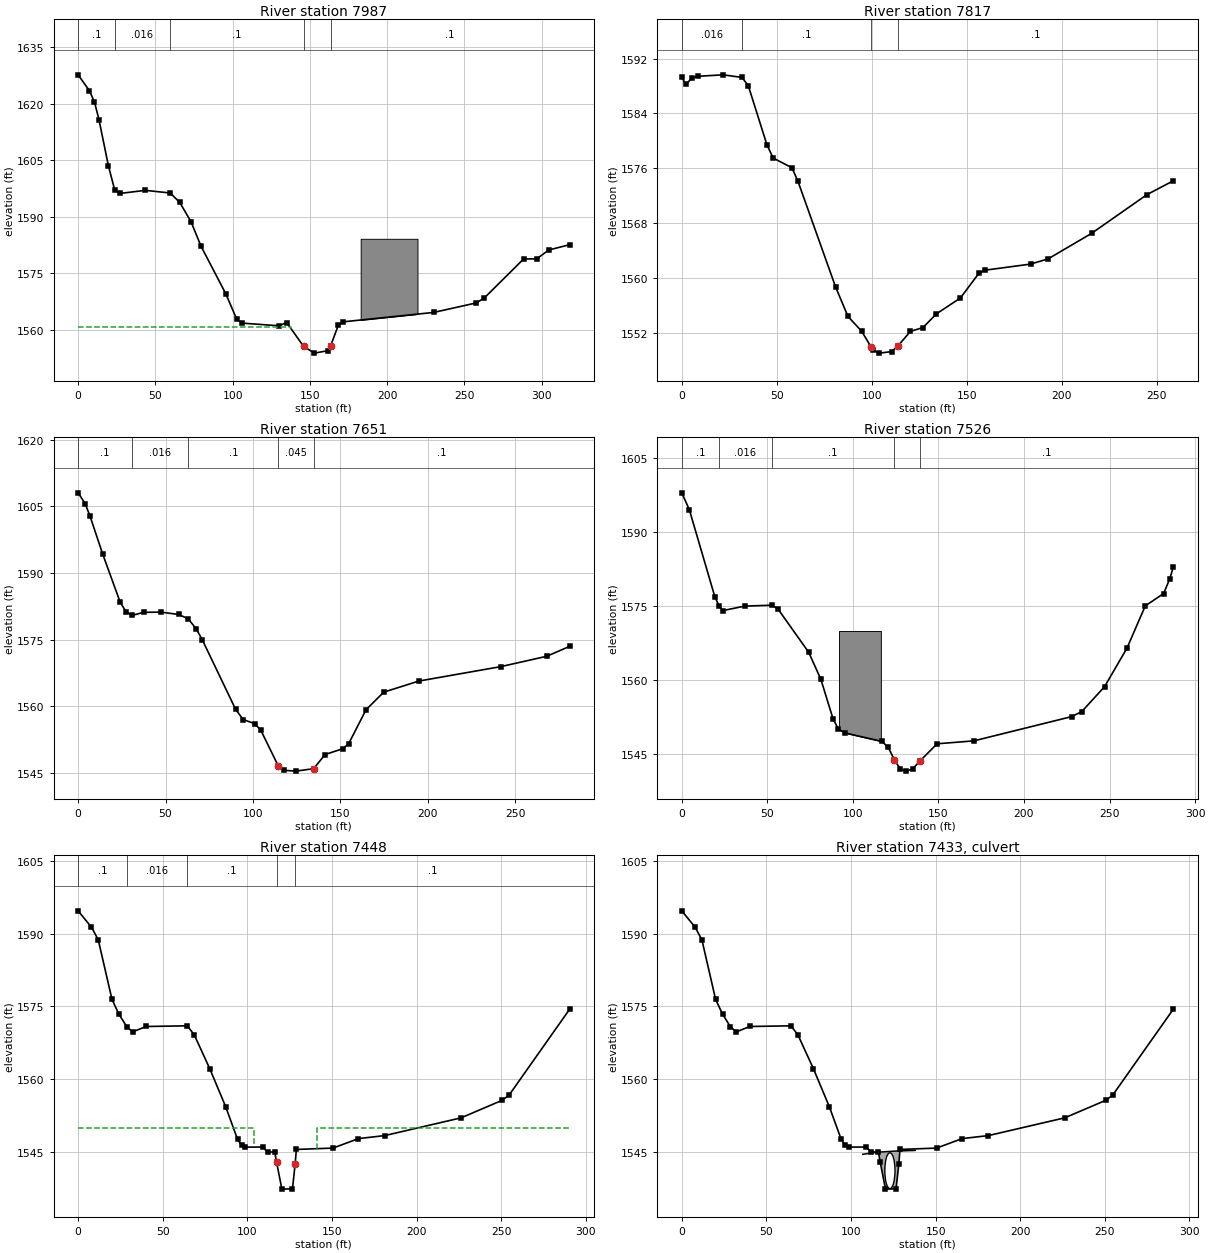
Type RM Length L Ch R = 1 ,7987    ,168.5,169.8,171
BEGIN DESCRIPTION:
Channel burned from survey ID:  BER108BD
END DESCRIPTION:
XS GIS Cut Line= 3
1991801.90877718237736.7119339431991786.57002766237512.766190921
1991726.74890452237440.674068168
#Sta/Elev= 30
       0  1627.6     7.3 1623.41    10.6  1620.4    13.5 1615.73    19.6 1603.52
    23.7 1597.06      27 1596.18    43.5    1597    59.6  1596.3    65.8  1593.8
    73.1 1588.67    79.6 1582.16    95.6  1569.6   102.7 1562.84     106 1561.84
     1301561.124     1351561.994     1461555.642     1531553.884     1621554.557
  163.46 1555.83   168.4 1561.24   171.7 1562.18   230.2 1564.67   257.7 1567.18
   262.8 1568.45   288.4 1578.83   296.8 1578.84   304.7 1581.21   318.1  1582.6
#Mann= 5 ,-1 , 0
       0      .1       0    23.7    .016       0    59.6      .1       0
     146    .045       0  163.46      .1       0
#XS Ineff= 2 , 0
             138 1560.86     174         1560.86
Permanent Ineff=
       F       F
#Block Obstruct= 1 ,-1
   182.9  219.66 1584.17
Bank Sta=146,163.46
XS Rating Curve= 0 ,0
Exp/Cntr(USF)=0,0
Exp/Cntr=0.5,0.3

Type RM Length L Ch R = 1 ,7817    ,165.3,166.8,168.5
XS GIS Cut Line= 2
1991953.79510116237701.9847409371991969.18805121237443.725245647
#Sta/Elev= 30
       0 1589.31     2.1 1588.23     5.4 1589.14     8.7 1589.41    21.8 1589.62
    31.7 1589.24      35 1588.05    44.8 1579.44    48.1 1577.48      58 1576.06
    61.2 1574.06      81 1558.65    87.5 1554.36    94.7 1552.21    99.8 1549.84
   100.7 1549.42     104 1549.01   110.5 1549.23   113.8 1550.06   120.4 1552.19
     127 1552.74     134 1554.73   146.7 1557.06   156.6 1560.73   159.8 1561.12
   183.6    1562   192.9 1562.77   215.7 1566.48   244.9 1572.14   258.7 1574.15
#Mann= 4 ,-1 , 0
       0    .016       0    31.7      .1       0    99.8    .045       0
   113.8      .1       0
Bank Sta=99.8,113.8
XS Rating Curve= 0 ,0
Exp/Cntr(USF)=0,0
Exp/Cntr=0.3,0.1

Type RM Length L Ch R = 1 ,7651    ,123.7,124.8,127.2
XS GIS Cut Line= 2
1992099.17296275237746.453263304 1992155.6137796237471.090490181
#Sta/Elev= 30
       0 1608.01       4  1605.6     6.8 1602.78      14 1594.29    24.1 1583.35
    27.4 1581.27    30.8 1580.42    37.5 1581.12    47.5 1581.16    57.6 1580.63
      63 1579.65    67.6 1577.37      71 1574.96    90.1 1559.28    94.4 1556.99
   101.1 1556.05   104.5 1554.59   114.5 1546.54   117.9 1545.56   124.5 1545.38
   134.7 1545.93   141.3 1549.12   151.3 1550.41   154.7 1551.52   164.7  1559.2
   174.8 1563.15   194.9 1565.65   241.8  1568.9     268 1571.22   281.1 1573.45
#Mann= 5 ,-1 , 0
       0      .1       0    30.8    .016       0      63      .1       0
   114.5    .045       0   134.7      .1       0
Bank Sta=114.5,134.7
XS Rating Curve= 0 ,0
Exp/Cntr(USF)=0,0
Exp/Cntr=0.3,0.1

Type RM Length L Ch R = 1 ,7526    ,75.9,78.9,80.4
XS GIS Cut Line= 2
1992194.95131861237748.163591088 1992309.5432801237484.773112448
#Sta/Elev= 30
       0 1597.88     4.4  1594.5    19.3 1576.89    21.8 1574.98      24 1574.06
    36.8 1574.97    52.6 1575.15    56.2  1574.4    74.2 1565.62    81.3 1560.15
    88.4 1552.18    91.6 1550.05    95.6  1549.3     117  1547.6   120.6 1546.43
   124.2 1543.92   127.8 1541.96   131.3 1541.59   134.9 1542.02     139 1543.57
   149.2 1547.12   170.7 1547.71   227.9 1552.62   233.8 1553.64   247.1 1558.68
   260.2 1566.47   270.9 1575.02   281.6 1577.51   285.2 1580.49   287.2 1582.78
#Mann= 5 ,-1 , 0
       0      .1       0    21.8    .016       0    52.6      .1       0
   124.2    .045       0     139      .1       0
#Block Obstruct= 1 ,-1
   91.91  116.35 1569.94
Bank Sta=124.2,139
XS Rating Curve= 0 ,0
Exp/Cntr(USF)=0,0
Exp/Cntr=0.5,0.3

Type RM Length L Ch R = 1 ,7448    ,46.2,46.5,46.3
BEGIN DESCRIPTION:
Channel burned from survey ID:  BER102CU
END DESCRIPTION:
XS GIS Cut Line= 2
1992240.59485919237768.6346292261992410.37672012237533.081416763
#Sta/Elev= 30
       0 1594.74     7.9 1591.36    11.9 1588.76      20 1576.47    24.1 1573.43
    28.8  1570.8    32.2 1569.76    40.2 1570.87    64.5 1571.01    68.6 1569.17
    77.8 1562.16    87.2 1554.32    94.2  1547.6    96.6 1546.33    98.9 1545.98
     109 1545.99     112 1544.96  116.18 1544.96   117.3 1542.84  120.39 1537.31
  126.66 1537.38  128.28 1542.58  128.96  1545.5   150.6 1545.78   165.6 1547.73
   181.2 1548.36   226.3 1552.02   250.5 1555.63   254.6 1556.68   290.4 1574.41
#Mann= 5 ,-1 , 0
       0      .1       0    28.8    .016       0    64.5      .1       0
   117.3    .045       0  128.28      .1       0
#XS Ineff= 4 ,-1
       0     104    1550     104     107  1544.9     138     141 1545.19
     141     290    1550
Permanent Ineff=
       F       F       F       F
Bank Sta=117.3,128.28
XS Rating Curve= 0 ,0
Exp/Cntr(USF)=0,0
Exp/Cntr=0.5,0.3

Type RM Length L Ch R = 2 ,7433    ,,,
BEGIN DESCRIPTION:
Priavte Drive
Survey ID: BER100
END DESCRIPTION:
Bridge Culvert--1,0,-1,-1, 0
Deck Dist Width WeirC Skew NumUp NumDn MinLoCord MaxHiCord MaxSubmerge Is_Ogee
11,20,2.6,0, 4, 7, , , 0.98, 0, 0,0,,
     107     115     126     138
1544.4951544.917 1545.161545.296
                                
     107     115     126     138     147     155     160
1544.4951544.917 1545.161545.2961546.1221546.122    1546
                                                        
BR Coef=-1 , 1 , 0 ,, 0 ,,,0.8,0,1.2,0,
WSPro=,,,, 1 ,,,, 0 ,,,, 0 ,,,,-1 ,-1 ,-1 , 0 , 0 , 0 , 0 , 0
Culvert=5,7.4,6,20,0.019,0.5,1,41,1,1537.416,123,1536.839,130,Culvert #1  , 0 ,11
     123     130
BC Culvert Barrel=1,Barrel1,0
Culvert Bottom n=0.019
BC Design=,, 0 ,, 0 ,,,,,,
BC Use User HTab Curves=0
BC User HTab FreeFlow(D)= 0

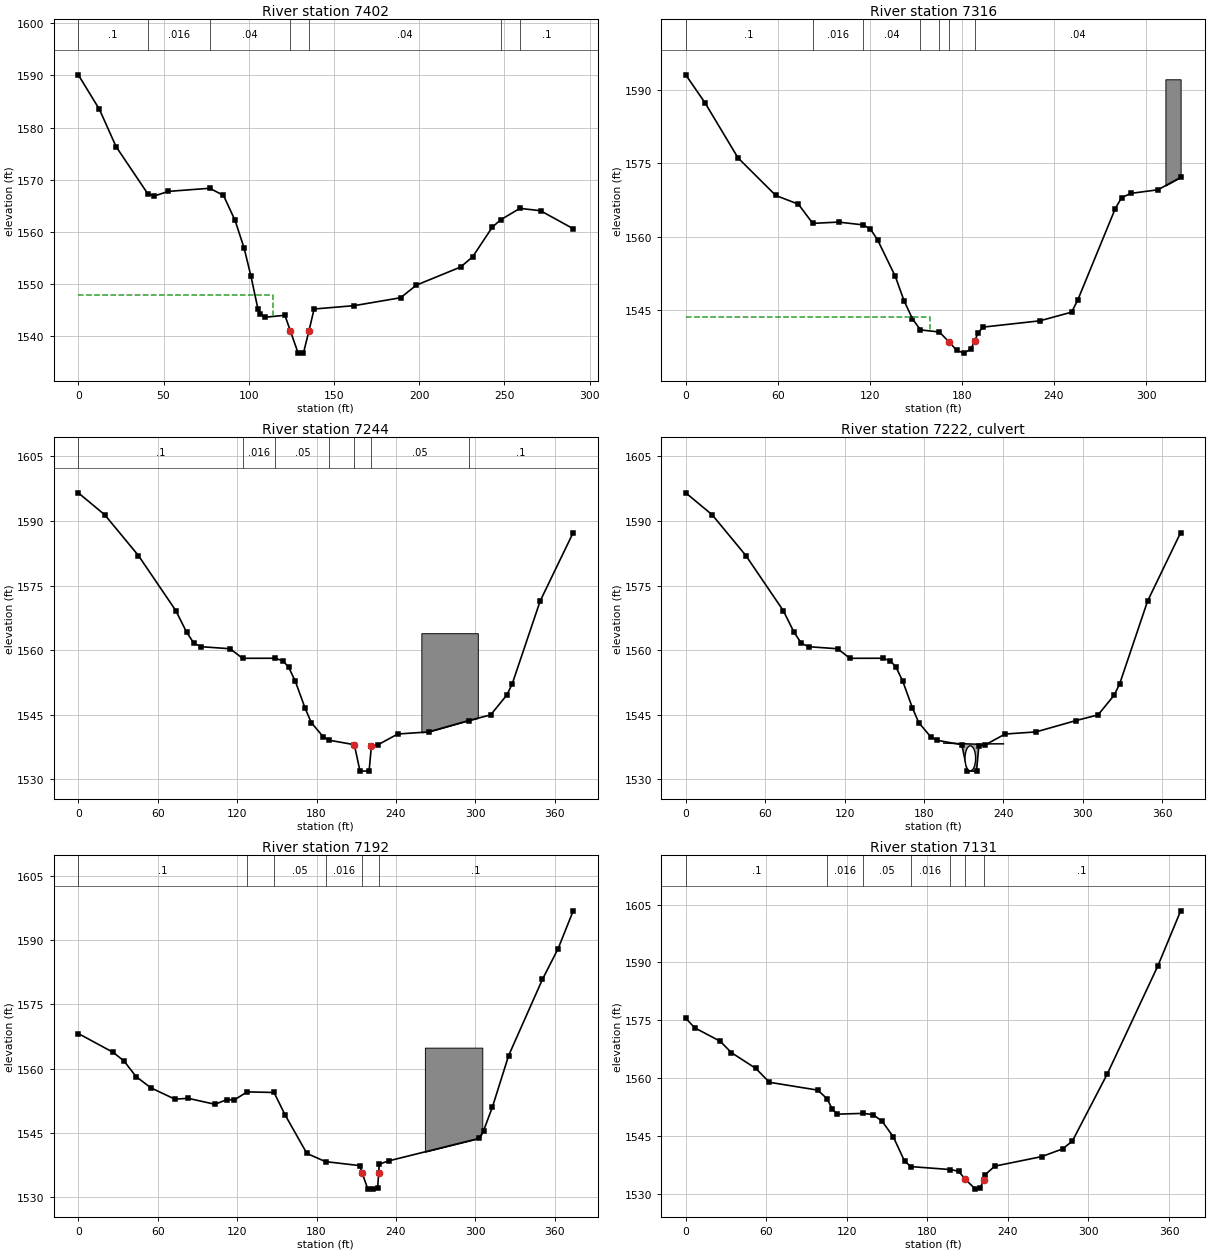
Type RM Length L Ch R = 1 ,7402    ,85.5,85.6,86.1
BEGIN DESCRIPTION:
Channel burned from survey ID:  BER098CD
END DESCRIPTION:
XS GIS Cut Line= 2
1992275.82470572 237798.504534221992445.60656665237562.951321757
#Sta/Elev= 30
       0 1590.11    12.4 1583.49    22.2 1576.34    40.7 1567.36    44.7 1566.91
    52.8 1567.78    77.1 1568.38    85.2 1567.01      92 1562.21    97.3 1556.91
   101.3 1551.55   105.4 1545.27   106.8 1544.38   109.4 1543.67  121.24 1544.05
  124.35 1541.12     129  1536.8  132.13 1536.84  135.37 1541.12  138.37 1545.25
     162  1545.9   189.1 1547.41   198.4 1549.83   224.3 1553.29   231.4 1555.25
   242.9 1560.92   247.8 1562.34   259.1 1564.53   271.2 1564.08   290.4 1560.63
#Mann= 7 ,-1 , 0
       0      .1       0    40.7    .016       0    77.1     .04       0
  124.35    .045       0  135.37     .04       0   247.8    .016       0
   259.1      .1       0
#XS Ineff= 3 ,-1
       0     114    1548     114     121  1541.4     138 290.364  1542.9
Permanent Ineff=
       F       F       F
Bank Sta=124.35,135.37
XS Rating Curve= 0 ,0
Exp/Cntr(USF)=0,0
Exp/Cntr=0.5,0.3

Type RM Length L Ch R = 1 ,7316    ,72,72,72.4
XS GIS Cut Line= 2
 1992319.8052468237878.1485026241992513.07228632237619.889007335
#Sta/Elev= 30
       0 1593.04    12.5 1587.37    34.1 1576.09    58.7 1568.43    73.4 1566.66
    82.8 1562.74    99.7    1563   115.6 1562.43   120.3  1561.6     125 1559.41
   136.6 1551.92   142.3 1546.96   147.8 1543.25     153 1541.01   165.3 1540.58
   171.9 1538.47   176.5 1536.88   181.2 1536.27   185.8 1537.08   188.3 1538.69
   190.6 1540.45   193.9 1541.58   230.8 1542.86   251.5 1544.63   255.4 1547.01
     280 1565.77   284.1 1567.99   290.2 1568.86   307.8 1569.59   322.6 1572.13
#Mann= 7 ,-1 , 0
       0      .1       0    82.8    .016       0   115.6     .04       0
     153    .016       0   165.3     .04       0   171.9    .045       0
   188.3     .04       0
#XS Ineff= 2 , 0
          159.13 1543.72
Permanent Ineff=
       F       F
#Block Obstruct= 1 ,-1
  312.65  322.57 1592.13
Bank Sta=171.9,188.3
XS Rating Curve= 0 ,0
Exp/Cntr(USF)=0,0
Exp/Cntr=0.5,0.3

Type RM Length L Ch R = 1 ,7244    ,51.8,51.6,51.6
BEGIN DESCRIPTION:
Channel burned from survey ID:  BER092CU
END DESCRIPTION:
XS GIS Cut Line= 3
1992350.72363385237959.8304185631992433.32021484237845.112944961
1992574.04031579237660.035420883
#Sta/Elev= 30
       0 1596.54      20 1591.43    45.4 1581.98    73.7 1569.17    81.8 1564.17
    87.4 1561.57      93 1560.79   114.7 1560.32   124.1  1558.1   148.9 1558.11
   154.6 1557.51   158.9 1556.03     164 1552.73   171.3 1546.54     176 1543.17
     185 1539.88   189.7 1539.06  208.53 1538.03   212.8 1531.92  219.69 1531.89
  221.44 1537.77   226.2 1537.98   241.3 1540.51   264.6    1541   294.9 1543.64
   311.5 1544.95   323.8 1549.59   327.9 1552.24   348.9 1571.39   373.9 1587.31
#Mann= 7 ,-1 , 0
       0      .1       0   124.1    .016       0   148.9     .05       0
   189.7    .016       0  208.53    .045       0  221.44     .05       0
   294.9      .1       0
#XS Ineff= 2 ,-1
       0     201 1538.25     228 373.858  1538.2
Permanent Ineff=
       F       F
#Block Obstruct= 1 ,-1
  259.16  301.82 1563.93
Bank Sta=208.53,221.44
XS Rating Curve= 0 ,0
Exp/Cntr(USF)=0,0
Exp/Cntr=0.5,0.3

Type RM Length L Ch R = 2 ,7222    ,,,
BEGIN DESCRIPTION:
Private Drive
Survey ID: BER090
Raised the top of road elevations from survey by 0.5ft because of low railing on the culvert face
END DESCRIPTION:
Bridge Culvert--1,0,-1,-1, 0
Deck Dist Width WeirC Skew NumUp NumDn MinLoCord MaxHiCord MaxSubmerge Is_Ogee
16,32,2.6,0, 4, 4, , , 0.98, 0, 0,0,,
     195     222     231     240
1538.4121538.1241538.2281538.228
                                
     195     222     231     240
1538.4121538.1241538.2281538.228
                                
BR Coef=-1 , 1 , 0 ,, 0 ,,,0.8,0,1.2,0,
WSPro=,,,, 1 ,,,, 0 ,,,, 0 ,,,,-1 ,-1 ,-1 , 0 , 0 , 0 , 0 , 0
Culvert=5,5.8,8,31,0.019,0.5,1,41,1,1531.959,215,1531.861,218,Culvert #1  , 0 ,16
     215     218
BC Culvert Barrel=1,Barrel1,0
Culvert Bottom n=0.019
BC Design=,, 0 ,, 0 ,,,,,,
BC Use User HTab Curves=0
BC User HTab FreeFlow(D)= 0

Type RM Length L Ch R = 1 ,7192    ,62.2,61.3,59.9
BEGIN DESCRIPTION:
Channel burned from survey ID:  BER088CD
END DESCRIPTION:
XS GIS Cut Line= 3
1992392.02192434237990.4217448561992474.61850534237875.704271254
1992615.33860629237690.626747176
#Sta/Elev= 30
       0  1568.2    26.5 1563.77    34.6 1561.76    43.6 1558.16    54.8 1555.52
    72.9 1552.88    83.1 1553.06   103.3 1551.67   112.2 1552.77   117.8 1552.68
   127.6 1554.57   147.9 1554.43   156.1 1549.26   172.7 1540.19   186.8 1538.28
  212.66 1537.35  214.58 1535.52  218.68  1531.9  222.34 1531.86  226.12 1532.04
  226.89 1535.52  227.34 1537.68   234.4 1538.45   302.9 1543.72   306.2 1545.54
   312.8 1550.99   325.1 1563.05   350.6 1580.82   362.4 1587.97   373.9 1596.85
#Mann= 6 ,-1 , 0
       0      .1       0   127.6    .016       0   147.9     .05       0
   186.8    .016       0  214.58    .045       0  226.89      .1       0
#XS Ineff= 2 ,-1
       0     211  1536.2     230 373.858  1536.2
Permanent Ineff=
       F       F
#Block Obstruct= 1 ,-1
  261.84   305.2  1564.9
Bank Sta=214.58,226.89
XS Rating Curve= 0 ,0
Exp/Cntr(USF)=0,0
Exp/Cntr=0.5,0.3

Type RM Length L Ch R = 1 ,7131    ,50.7,49.7,48.6
XS GIS Cut Line= 3
 1992463.4727806238033.7883309111992531.88589194237915.775713858
1992649.89850899237715.667363204
#Sta/Elev= 30
       0 1575.54     6.7 1573.05    25.7 1569.56      34 1566.61    52.2 1562.52
    62.3 1558.92    98.4 1556.88   105.3 1554.64   109.1 1552.02   112.9 1550.65
     132 1550.85   139.5 1550.54   146.3 1548.81   154.7 1544.73   163.1 1538.38
   167.9 1537.04   196.6 1536.29   203.3 1535.86     208 1533.83   215.8  1531.2
   219.4 1531.47  221.931533.584   223.2 1534.97   230.2 1537.16   265.1 1539.63
   280.8 1541.64     288 1543.65   314.1 1561.13   351.8 1589.19   368.7  1603.4
#Mann= 7 ,-1 , 0
       0      .1       0   105.3    .016       0     132     .05       0
   167.9    .016       0   196.6     .05       0     208    .045       0
  221.93      .1       0
Bank Sta=208,221.93
XS Rating Curve= 0 ,0
Exp/Cntr(USF)=0,0
Exp/Cntr=0.5,0.3