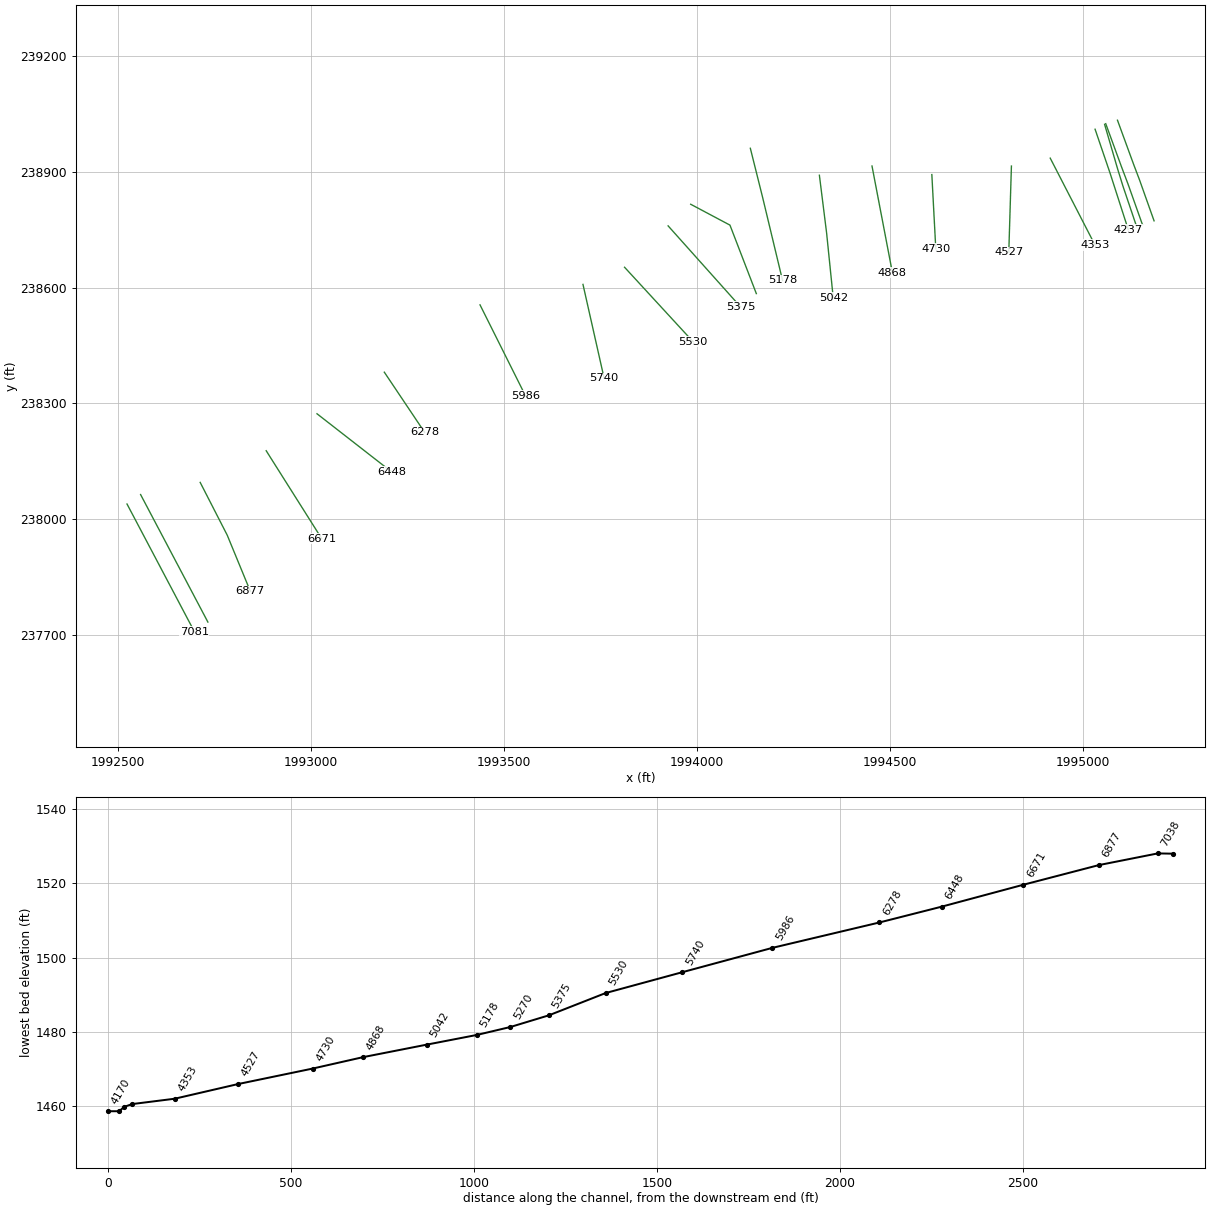
HEC-RAS study BEECHRN.prj: BEECHRN

--- BEECHRN.g01 (geometry) --- (continued)

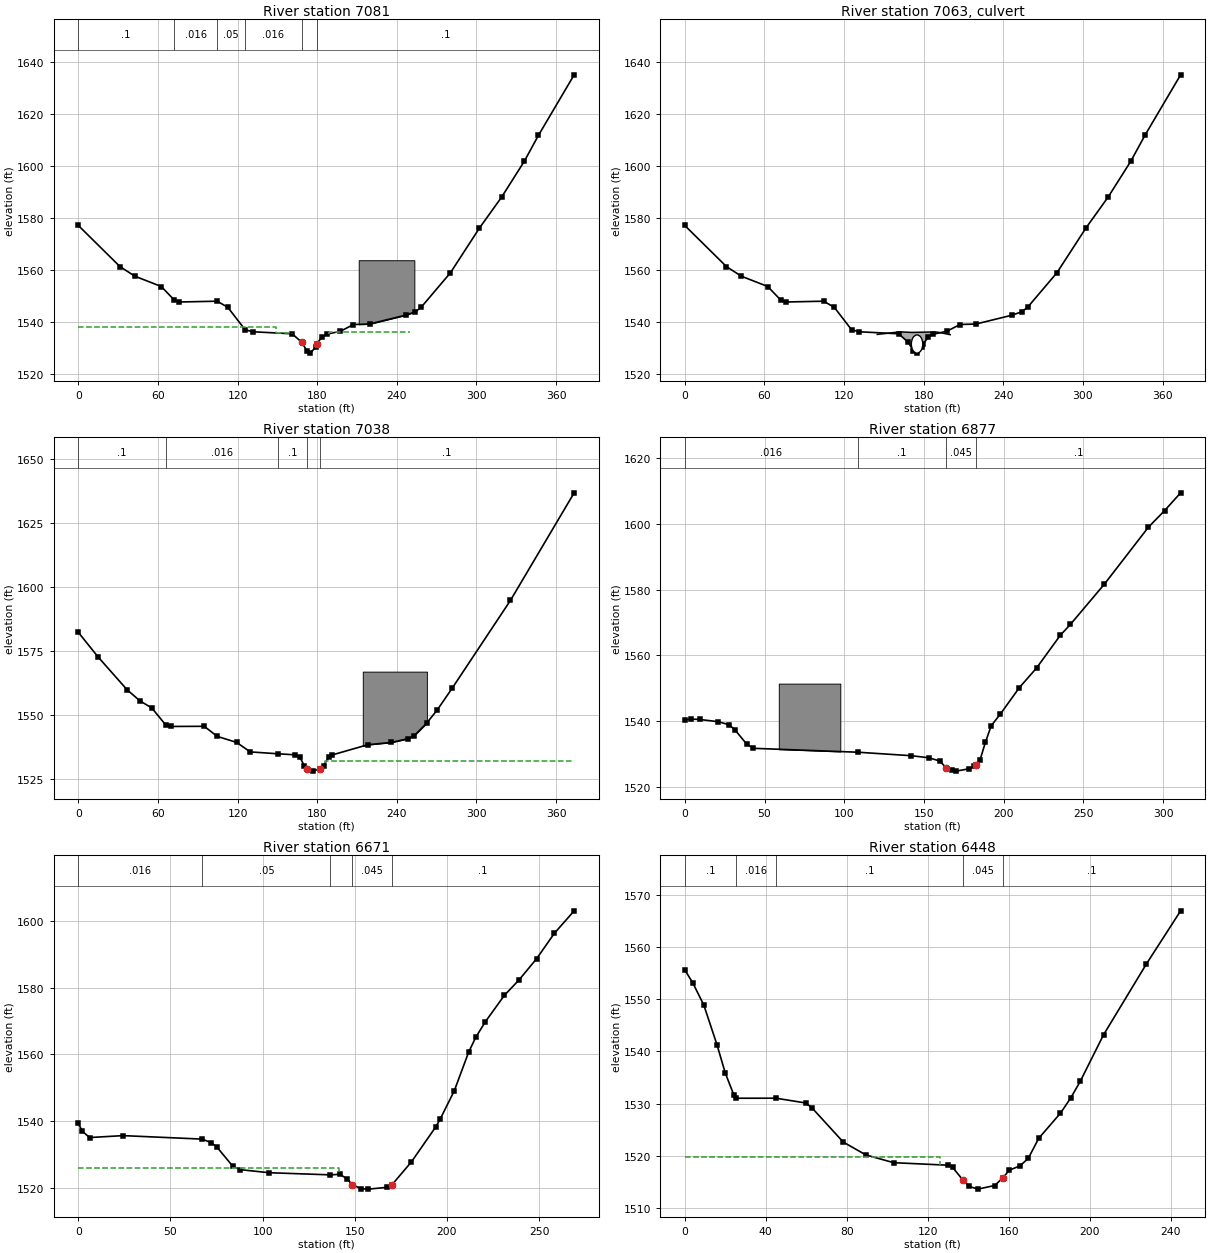
Type RM Length L Ch R = 1 ,7081    ,42.6,42.8,42.7
BEGIN DESCRIPTION:
Channel burned from survey ID: 54089BER082CU
END DESCRIPTION:
XS GIS Cut Line= 2
1992523.56462741238039.3678669271992697.93518728237708.981542953
#Sta/Elev= 30
       0 1577.05    31.4 1561.21    42.6 1557.52    62.5 1553.55    72.2 1548.38
    76.1 1547.58   104.6 1547.89   112.6 1545.55   125.7 1536.88   131.6 1536.11
   161.1 1535.34   168.4 1532.05  172.11 1528.87   174.91527.888  178.97  1530.3
   179.8 1531.55   183.5 1534.06   187.2 1535.18   197.5 1536.31   207.3 1538.91
   219.4  1539.1   246.6 1542.51     254 1543.84   258.3 1545.54   280.4 1558.85
   302.2 1576.04     319 1588.02     336 1601.75   346.7 1611.77   373.6 1635.08
#Mann= 6 ,-1 , 0
       0      .1       0    72.2    .016       0   104.6     .05       0
   125.7    .016       0   168.4    .045       0   179.8      .1       0
#XS Ineff= 3 ,-1
       0     149    1538     149     161 1535.73     189     250    1536
Permanent Ineff=
       F       F       F
#Block Obstruct= 1 ,-1
  211.27  253.19 1563.67
Bank Sta=168.4,179.8
XS Rating Curve= 0 ,0
Exp/Cntr(USF)=0,0
Exp/Cntr=0.5,0.3

Type RM Length L Ch R = 2 ,7063    ,,,
BEGIN DESCRIPTION:
Private Dr
Survey ID: BER080
Raised the top of road elevations from survey by 1ft because of low railing on the culvert face
END DESCRIPTION:
Bridge Culvert--1,0,-1,-1, 0
Deck Dist Width WeirC Skew NumUp NumDn MinLoCord MaxHiCord MaxSubmerge Is_Ogee
12,19,2.6,0, 6, 6, , , 0.98, 0, 0,0,,
     145     162     171     183     190     200
1535.0861536.0861535.8681535.9971535.9971534.997
                                                
     145     162     171     183     190     200
1535.0861536.0861535.8681535.9971535.9971534.997
                                                
BR Coef=-1 , 1 , 0 ,, 0 ,,,0.8,0,1.2,0,
WSPro=,,,, 1 ,,,, 0 ,,,, 0 ,,,,-1 ,-1 ,-1 , 0 , 0 , 0 , 0 , 0
Culvert=4,7,8.6,20,0.019,0.5,1,29,1,1527.892,175,1527.987,177,Culvert #1  , 0 ,10
     175     177
BC Culvert Barrel=1,Barrel1,0
Culvert Bottom n=0.019
BC Design=,, 0 ,, 0 ,,,,,,
BC Use User HTab Curves=0
BC User HTab FreeFlow(D)= 0

Type RM Length L Ch R = 1 ,7038    ,161.7,161.1,159.8
BEGIN DESCRIPTION:
Channel burned from survey ID: BER078CD
END DESCRIPTION:
XS GIS Cut Line= 2
1992558.74465265238063.8409279621992733.11521252237733.454603988
#Sta/Elev= 30
       0 1582.16    14.8  1572.6    36.8  1559.7    46.4 1555.42    55.4  1552.6
    65.8 1546.03    70.2 1545.41    94.9 1545.47   104.6 1541.54   119.2 1539.19
   129.6 1535.47   150.8 1534.72     163 1534.34   166.7 1533.61   170.4 1529.96
   172.6 1528.92   176.91527.963   182.3 1528.96   184.8  1530.1   188.9 1533.67
   190.9 1534.23   218.1 1538.27   235.8 1539.17   248.3 1540.61   252.8 1541.65
   262.5 1546.73   270.5  1551.9   281.7 1560.35   325.6 1594.64   373.6 1636.65
#Mann= 5 ,-1 , 0
       0      .1       0    65.8    .016       0   150.8      .1       0
   172.6    .045       0   182.3      .1       0
#XS Ineff= 2 , 0
             167  1531.8     186          1531.8
Permanent Ineff=
       F       F
#Block Obstruct= 1 ,-1
  214.33  262.63 1566.82
Bank Sta=172.6,182.3
XS Rating Curve= 0 ,0
Exp/Cntr(USF)=0,0
Exp/Cntr=0.5,0.3

Type RM Length L Ch R = 1 ,6877    ,204.2,205.9,208.8
XS GIS Cut Line= 3
1992713.18063698238095.3601311121992783.30407609237958.533908442
1992843.16554851237813.156046856
#Sta/Elev= 30
       0 1540.36       4 1540.66     9.4 1540.53      21 1539.85    27.8 1538.93
    31.5 1537.34    38.8 1533.05      43 1531.76   108.6 1530.57   142.1 1529.51
   153.1 1528.88   159.9  1527.9   163.8 1525.92   167.3 1525.04   170.2 1524.82
     178 1525.51   181.5 1526.24   182.8 1526.82   185.1  1528.1   188.6 1533.65
   192.2 1538.63   197.9 1542.16   209.9 1550.25   220.6 1556.17   235.6 1566.18
   241.9 1569.46   263.2 1581.71   290.8 1599.02   300.9 1604.03     311 1609.47
#Mann= 4 ,-1 , 0
       0    .016       0   108.6      .1       0   163.8    .045       0
   182.8      .1       0
#Block Obstruct= 1 ,-1
   58.95   97.54 1551.44
Bank Sta=163.8,182.8
XS Rating Curve= 0 ,0
Exp/Cntr(USF)=0,0
Exp/Cntr=0.3,0.1

Type RM Length L Ch R = 1 ,6671    ,218.6,223.1,227.5
XS GIS Cut Line= 2
1992884.21341531238177.4558647141993027.88094912237949.982269525
#Sta/Elev= 30
       0 1539.25     2.2 1536.91     6.1 1535.03    24.3 1535.61    67.3 1534.56
      72  1533.5      75 1532.29    83.7 1526.48    87.5 1525.41   103.5 1524.48
   136.8 1523.83   141.9    1524   145.7 1522.67   148.7 1520.89   153.4 1519.66
   157.4 1519.55   167.7  1520.1   170.1 1520.82   180.7 1527.72   193.9 1538.22
   196.3 1540.55     204 1549.11   211.7 1560.59   215.6  1565.1   220.9 1569.85
   231.1 1577.68   239.1 1582.35   248.6 1588.69   258.3 1596.36     269 1603.08
#Mann= 5 ,-1 , 0
       0    .016       0    67.3     .05       0   136.8      .1       0
   148.7    .045       0   170.1      .1       0
#XS Ineff= 2 , 0
           141.3 1525.93
Permanent Ineff=
       F       F
Bank Sta=148.7,170.1
XS Rating Curve= 0 ,0
Exp/Cntr(USF)=0,0
Exp/Cntr=0.3,0.1

Type RM Length L Ch R = 1 ,6448    ,174.5,170.2,166.1
XS GIS Cut Line= 2
1993015.90865463238273.2342205831993209.17569415238122.725375646
#Sta/Elev= 30
       0 1555.61       4 1553.08     9.4 1548.88    15.9 1541.29      20 1535.87
    24.2 1531.72    25.4 1531.05      45 1531.06    59.8 1530.14    62.8 1529.23
    78.3 1522.66    89.5  1520.2   103.2 1518.72   129.9 1518.24   132.3 1517.83
   137.5 1515.37   140.6 1514.18   144.8 1513.66   153.1 1514.35   157.3 1515.85
   160.3 1517.27   165.6 1518.11   169.7 1519.53   174.9 1523.39   185.6 1528.18
   190.7  1531.1   195.4 1534.28   206.9 1543.18   228.1 1556.75     245 1566.91
#Mann= 5 ,-1 , 0
       0      .1       0    25.4    .016       0      45      .1       0
   137.5    .045       0   157.3      .1       0
#XS Ineff= 2 , 0
          126.06 1519.87
Permanent Ineff=
       F       F
Bank Sta=137.5,157.3
XS Rating Curve= 0 ,0
Exp/Cntr(USF)=0,0
Exp/Cntr=0.3,0.1

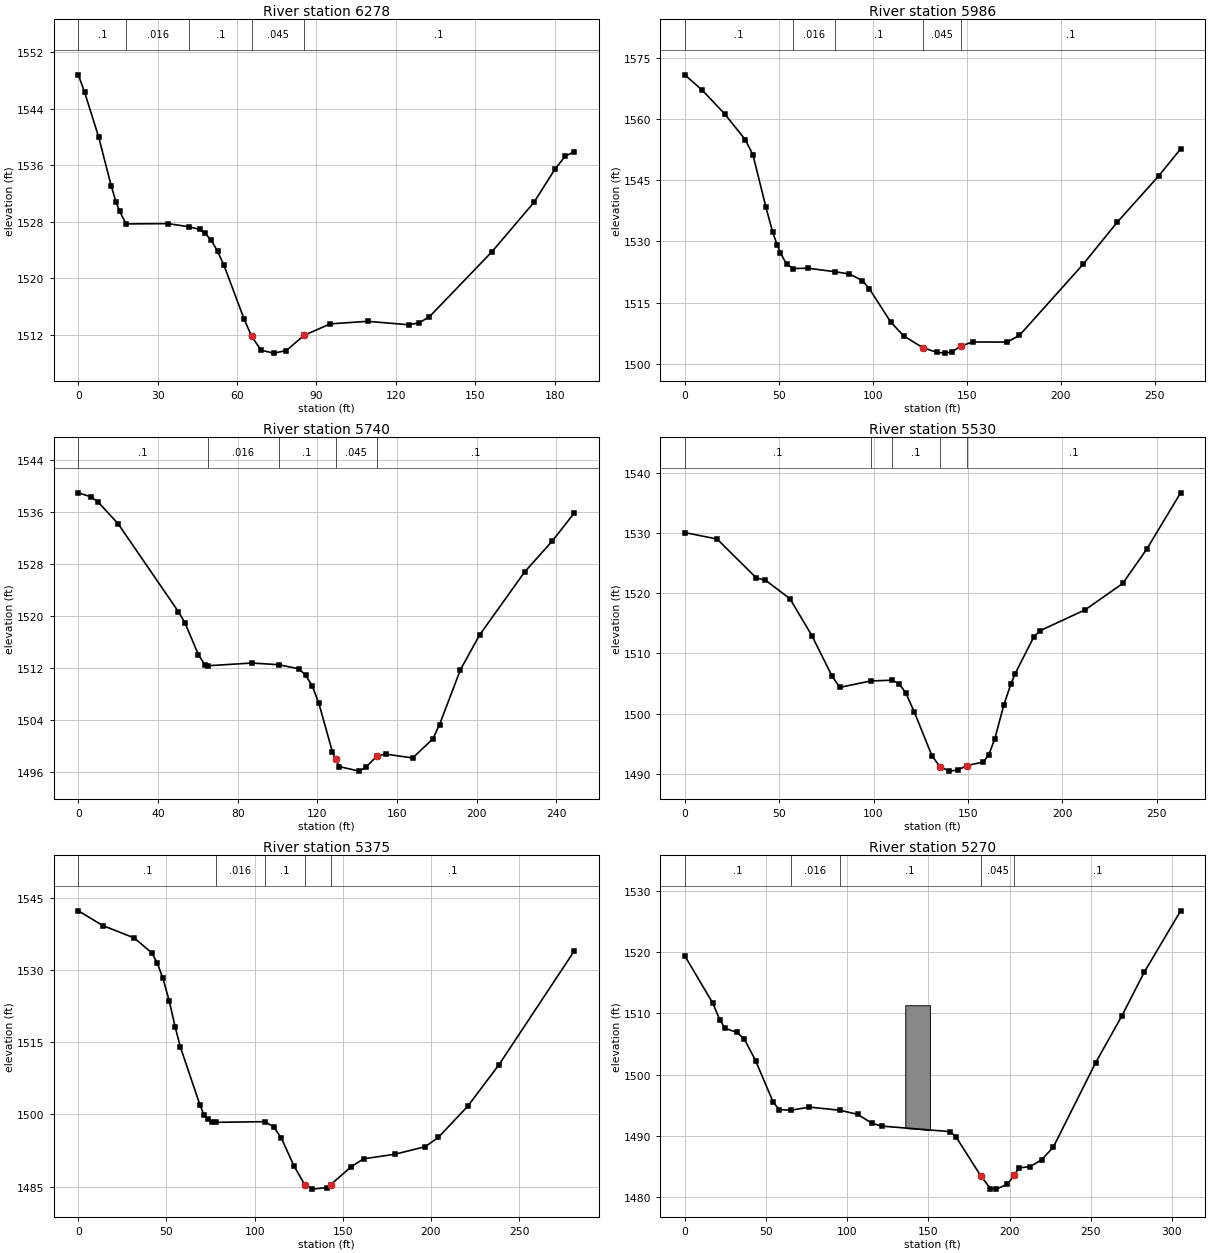
Type RM Length L Ch R = 1 ,6278    ,293.6,292,290.2
Node Name=B
XS GIS Cut Line= 2
1993190.36208854238380.9848709351993294.69208332238225.345042648
#Sta/Elev= 30
       0  1548.8     2.4 1546.31     7.7 1539.98    12.4 1533.12    14.2 1530.85
    15.6 1529.47    18.1  1527.7    33.9 1527.74    41.8  1527.3    45.8 1526.93
    47.9 1526.36    50.2 1525.42    52.6 1523.85      55 1521.88    62.7 1514.19
    65.5 1511.79    69.1 1509.81    73.9 1509.41    78.6 1509.77    85.3 1511.92
    95.2 1513.55   109.3 1513.91   124.8 1513.43   128.7 1513.68   132.7 1514.56
   156.4 1523.79   172.2 1530.75   180.1 1535.42     184 1537.27   187.4 1537.92
#Mann= 5 ,-1 , 0
       0      .1       0    18.1    .016       0    41.8      .1       0
    65.5    .045       0    85.3      .1       0
Bank Sta=65.5,85.3
XS Rating Curve= 0 ,0
Exp/Cntr(USF)=0,0
Exp/Cntr=0.3,0.1

Type RM Length L Ch R = 1 ,5986    ,247.9,246.1,241.4
XS GIS Cut Line= 2
1993438.35961713238555.4383048391993556.37223418238319.413070734
#Sta/Elev= 30
       0 1570.91     9.4 1567.09    21.2 1561.33    32.2 1554.99    36.3 1551.23
    43.2 1538.37    46.8 1532.22    49.2 1529.15    50.9 1527.19    54.2 1524.39
    57.8 1523.37    65.6 1523.44    79.8 1522.59    87.6 1522.02    94.5 1520.42
    98.2 1518.42   109.6 1510.23   116.5 1506.83   126.7 1503.93   134.1  1502.8
   138.5  1502.6   142.2 1502.91   147.1 1504.38   153.2 1505.33   171.6 1505.32
   178.1 1506.95   211.9 1524.36   230.2 1534.76   252.2 1546.08   263.9 1552.72
#Mann= 5 ,-1 , 0
       0      .1       0    57.8    .016       0    79.8      .1       0
   126.7    .045       0   147.1      .1       0
Bank Sta=126.7,147.1
XS Rating Curve= 0 ,0
Exp/Cntr(USF)=0,0
Exp/Cntr=0.3,0.1

Type RM Length L Ch R = 1 ,5740    ,202.1,209.5,214.5
XS GIS Cut Line= 2
1993705.17075133238608.458466124 1993759.9012404238365.591920885
#Sta/Elev= 30
       0  1538.9     6.5 1538.27     9.9 1537.49    19.9 1534.17    50.2 1520.63
    53.6 1518.86    60.3 1513.97    63.7 1512.37    64.9 1512.28    87.2  1512.7
   100.6 1512.44   110.7 1511.81   114.1 1510.86   117.5 1509.16   120.8 1506.48
   127.6 1499.02  129.151497.963   130.9 1496.77     141 1496.06   144.4 1496.65
     150  1498.4   154.5 1498.67   167.9 1498.09     178 1501.01   181.4 1503.23
   191.9 1511.68   201.5 1517.01   224.1 1526.71   237.9 1531.44     249 1535.77
#Mann= 5 ,-1 , 0
       0      .1       0    64.9    .016       0   100.6      .1       0
  129.15    .045       0     150      .1       0
Bank Sta=129.15,150
XS Rating Curve= 0 ,0
Exp/Cntr(USF)=0,0
Exp/Cntr=0.3,0.1

Type RM Length L Ch R = 1 ,5530    ,155.1,155.2,154.8
XS GIS Cut Line= 2
1993812.92140168238652.9269884911993990.79549115 238459.65994897
#Sta/Elev= 30
       0 1530.07    17.1    1529    37.8 1522.56    42.7 1522.17    55.7 1519.09
    67.3 1512.98      78 1506.25    82.1 1504.36    98.4 1505.43     110 1505.56
   113.6 1504.93     117  1503.5   121.6 1500.28   130.9 1493.05   135.1 1491.21
   140.2 1490.46   144.8 1490.65   149.3 1491.38   158.2 1491.97   161.1 1493.21
   164.2 1495.78     169 1501.41   172.7 1504.88     175 1506.64     185  1512.8
   188.4  1513.8   212.2 1517.26     232 1521.62   244.7 1527.29   262.7 1536.67
#Mann= 5 ,-1 , 0
       0      .1       0    98.4    .016       0     110      .1       0
   135.1    .045       0   149.3      .1       0
Bank Sta=135.1,149.3
XS Rating Curve= 0 ,0
Exp/Cntr(USF)=0,0
Exp/Cntr=0.3,0.1

Type RM Length L Ch R = 1 ,5375    ,107.7,104.9,100.3
XS GIS Cut Line= 2
1993925.82411337238760.1537004031994113.29771864238550.524123602
#Sta/Elev= 30
       0 1542.31    13.9 1539.24    31.7 1536.68    41.7 1533.55    44.7 1531.53
      48 1528.25    51.6 1523.52    54.9 1518.18    57.9 1513.97    68.9 1502.04
    71.2 1499.92    73.5 1498.97    75.8 1498.35    78.2 1498.35   105.7 1498.49
   110.8 1497.41   115.2 1495.03   122.3 1489.29   128.4  1485.4   132.8 1484.47
   140.9 1484.79   143.2 1485.43   154.8 1489.13   161.8 1490.77   179.5 1491.72
   196.7 1493.29   204.1  1495.2   220.8 1501.68   238.5 1510.29   281.2 1533.93
#Mann= 5 ,-1 , 0
       0      .1       0    78.2    .016       0   105.7      .1       0
   128.4    .045       0   143.2      .1       0
Bank Sta=128.4,143.2
XS Rating Curve= 0 ,0
Exp/Cntr(USF)=0,0
Exp/Cntr=0.3,0.1

Type RM Length L Ch R = 1 ,5270    ,92.9,91.8,90
XS GIS Cut Line= 3
1993984.32734862238816.1624483811994086.06123782238762.116319743
1994154.41369463238584.611877647
#Sta/Elev= 30
       0 1519.36    17.3 1511.63    21.5 1508.97    24.7 1507.56    32.1 1506.89
    36.6 1505.82    43.6 1502.29    54.4 1495.54    58.1 1494.31    65.2 1494.19
    76.7 1494.71    95.3  1494.2   106.5 1493.53   115.2 1492.08   121.4 1491.61
   163.6 1490.71   167.1 1489.83   182.2 1483.55   188.2 1481.44   191.7 1481.34
   198.7 1482.12     2031483.638   205.8 1484.79   212.8 1485.02   219.8 1486.13
   226.9 1488.15   253.1 1501.97   269.1 1509.52   283.1 1516.75   305.4  1526.7
#Mann= 5 ,-1 , 0
       0      .1       0    65.2    .016       0    95.3      .1       0
   182.2    .045       0     203      .1       0
#Block Obstruct= 1 ,-1
  135.81  150.97 1511.31
Bank Sta=182.2,203
XS Rating Curve= 0 ,0
Exp/Cntr(USF)=0,0
Exp/Cntr=0.3,0.1

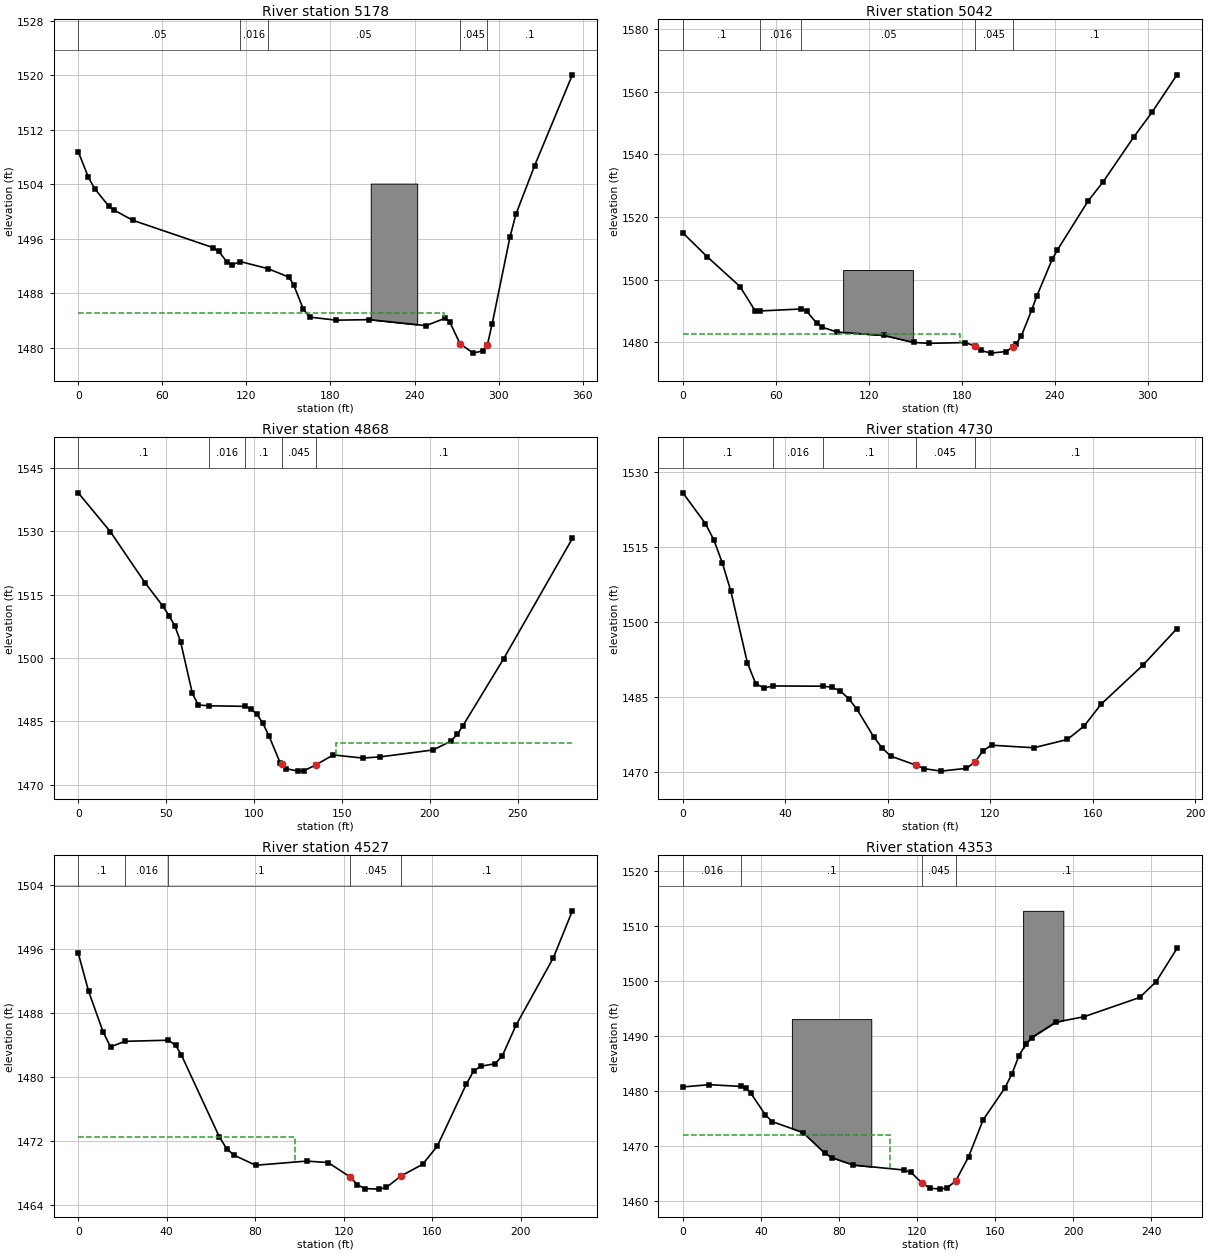
Type RM Length L Ch R = 1 ,5178    ,137.4,136.7,134
XS GIS Cut Line= 3
1994138.86230118238961.2617496911994171.24410572238831.734531506
1994222.37327079  238618.6963437
#Sta/Elev= 30
       0 1508.79     7.3    1505    11.7 1503.36    21.9 1500.76    25.2 1500.25
    38.8 1498.72    96.3 1494.69   100.1 1494.16   106.4 1492.55   109.8 1492.17
   115.6 1492.65   135.3 1491.61   150.3 1490.37   153.7 1489.25   160.5  1485.7
   165.2 1484.49   184.1 1484.04   207.7 1484.12   248.2 1483.24   261.7 1484.32
     265 1483.81   272.5 1480.57   281.9  1479.2   288.7 1479.55     292 1480.46
   295.4 1483.53     308 1496.19   312.3  1499.6   325.7 1506.76   352.6 1520.08
#Mann= 5 ,-1 , 0
       0     .05       0   115.6    .016       0   135.3     .05       0
   272.5    .045       0     292      .1       0
#XS Ineff= 2 , 0
          260.73 1485.08
Permanent Ineff=
       F       F
#Block Obstruct= 1 ,-1
  208.71  241.86  1504.1
Bank Sta=272.5,292
XS Rating Curve= 0 ,0
Exp/Cntr(USF)=0,0
Exp/Cntr=0.3,0.1

Type RM Length L Ch R = 1 ,5042    ,170.2,173.9,175.4
XS GIS Cut Line= 3
1994317.81437893238891.3852240911994336.56173946238741.406339876
1994353.60479448238574.384400637
#Sta/Elev= 30
       0 1514.95    15.7 1507.35    36.9 1497.83    46.8    1490    49.8 1490.05
    76.6 1490.68    79.9 1489.97    86.5 1486.11    89.8 1484.88    99.7 1483.32
   129.8 1482.24   149.3 1479.99   159.2 1479.72   182.3 1479.98   188.9 1478.82
   192.2 1477.47   198.8  1476.6   208.7 1477.11   213.2 1478.59   215.3 1479.59
   218.6  1482.2   225.2 1490.29   228.5 1494.78   238.4 1506.46   241.7 1509.41
   261.5 1525.02   271.4 1531.27   291.1 1545.52     303 1553.48     319 1565.35
#Mann= 5 ,-1 , 0
       0      .1       0    49.8    .016       0    76.6     .05       0
   188.9    .045       0   213.2      .1       0
#XS Ineff= 2 , 0
          178.65 1482.61
Permanent Ineff=
       F       F
#Block Obstruct= 1 ,-1
  103.47  148.51 1503.09
Bank Sta=188.9,213.2
XS Rating Curve= 0 ,0
Exp/Cntr(USF)=0,0
Exp/Cntr=0.3,0.1

Type RM Length L Ch R = 1 ,4868    ,139.6,137.8,136.2
XS GIS Cut Line= 2
1994454.15881913238915.245501125 1994506.9922897238639.148009729
#Sta/Elev= 30
       0 1539.05    18.2 1529.89    38.2 1517.67    48.2 1512.23    51.6 1510.01
    54.9 1507.62    58.2 1503.88    64.9 1491.65    68.3 1488.88    74.3 1488.69
      95 1488.56    98.3 1487.93   101.7 1486.65     105 1484.57   108.4 1481.66
     115 1475.08   115.7 1474.85   118.4 1473.81   125.1 1473.24   128.4 1473.32
   135.1 1474.71   145.1 1477.07   161.8 1476.33   171.8 1476.61   201.9 1478.25
   211.9 1480.31   215.6 1481.94   218.6 1483.82     242 1499.81   281.1 1528.26
#Mann= 5 ,-1 , 0
       0      .1       0    74.3    .016       0      95      .1       0
   115.7    .045       0   135.1      .1       0
#XS Ineff= 2 , 0
                          146.87         1479.94
Permanent Ineff=
       F       F
Bank Sta=115.7,135.1
XS Rating Curve= 0 ,0
Exp/Cntr(USF)=0,0
Exp/Cntr=0.3,0.1

Type RM Length L Ch R = 1 ,4730    ,203.5,203.3,201
XS GIS Cut Line= 2
1994609.25061985238893.0895295941994619.47645286238700.503007817
#Sta/Elev= 30
       0 1525.78     8.8 1519.65    12.1 1516.37    15.4 1511.78    18.7 1506.21
    25.2  1491.8    28.5 1487.58    31.8 1486.79    35.1 1487.19    54.8 1487.14
    58.1 1486.95    61.4 1486.21    64.7 1484.68      68 1482.52    74.5 1477.02
    77.8  1474.8    81.1 1473.18      91 1471.36    94.2 1470.66   100.8 1470.17
   110.7 1470.73     114 1471.96   117.2 1474.24   120.5 1475.35     137 1474.84
   150.1 1476.49   156.7  1479.2   163.2  1483.5   179.7 1491.39   192.9 1498.66
#Mann= 5 ,-1 , 0
       0      .1       0    35.1    .016       0    54.8      .1       0
      91    .045       0     114      .1       0
Bank Sta=91,114
XS Rating Curve= 0 ,0
Exp/Cntr(USF)=0,0
Exp/Cntr=0.3,0.1

Type RM Length L Ch R = 1 ,4527    ,167.4,173.5,181.3
XS GIS Cut Line= 2
1994815.47158565238915.2455011251994808.65436364238691.981480305
#Sta/Elev= 30
       0 1495.49     4.7 1490.71    11.3 1485.61    14.6 1483.79    21.1 1484.48
    40.8 1484.62    44.1 1483.96    46.6 1482.79    63.8 1472.54    67.1 1471.07
    70.4 1470.27    80.2    1469   103.2 1469.52     113 1469.34   122.9 1467.54
   126.2 1466.57   129.5 1466.09     136 1466.02   139.3 1466.23   145.9 1467.66
   155.7 1469.12   162.3 1471.38   175.4  1479.1   178.7 1480.75     182 1481.37
   188.5 1481.68   191.8 1482.71   197.9 1486.48   214.8 1494.91   223.4 1500.78
#Mann= 5 ,-1 , 0
       0      .1       0    21.1    .016       0    40.8      .1       0
   122.9    .045       0   145.9      .1       0
#XS Ineff= 2 , 0
           97.89 1472.49
Permanent Ineff=
       F       F
Bank Sta=122.9,145.9
XS Rating Curve= 0 ,0
Exp/Cntr(USF)=0,0
Exp/Cntr=0.3,0.1

Type RM Length L Ch R = 1 ,4353    ,119,116.4,114.7
XS GIS Cut Line= 2
1994916.02561029238935.6971671551995031.91838446238710.728840832
#Sta/Elev= 30
       0 1480.66    13.6 1481.07      30 1480.75    32.5  1480.4    34.9 1479.48
    42.2 1475.62    45.7 1474.36    61.5 1472.37    72.6 1468.64    76.3 1467.79
    87.4 1466.45   113.2 1465.55   116.9  1465.1   122.6 1463.15   126.5 1462.26
   131.6 1462.07   135.3  1462.3   139.7 1463.52   146.4 1467.98   153.8 1474.67
   164.9 1480.44   168.6 1483.07   172.2 1486.37   175.9 1488.56   178.6 1489.63
     191 1492.44   205.5 1493.43     234 1496.94   242.4 1499.79   253.1 1505.86
#Mann= 4 ,-1 , 0
       0    .016       0      30      .1       0   122.6    .045       0
   139.7      .1       0
#XS Ineff= 2 , 0
          106.31    1472
Permanent Ineff=
       F       F
#Block Obstruct= 2 ,-1
   55.86   96.52    1493  174.29  194.88  1512.7
Bank Sta=122.6,139.7
XS Rating Curve= 0 ,0
Exp/Cntr(USF)=0,0
Exp/Cntr=0.5,0.3

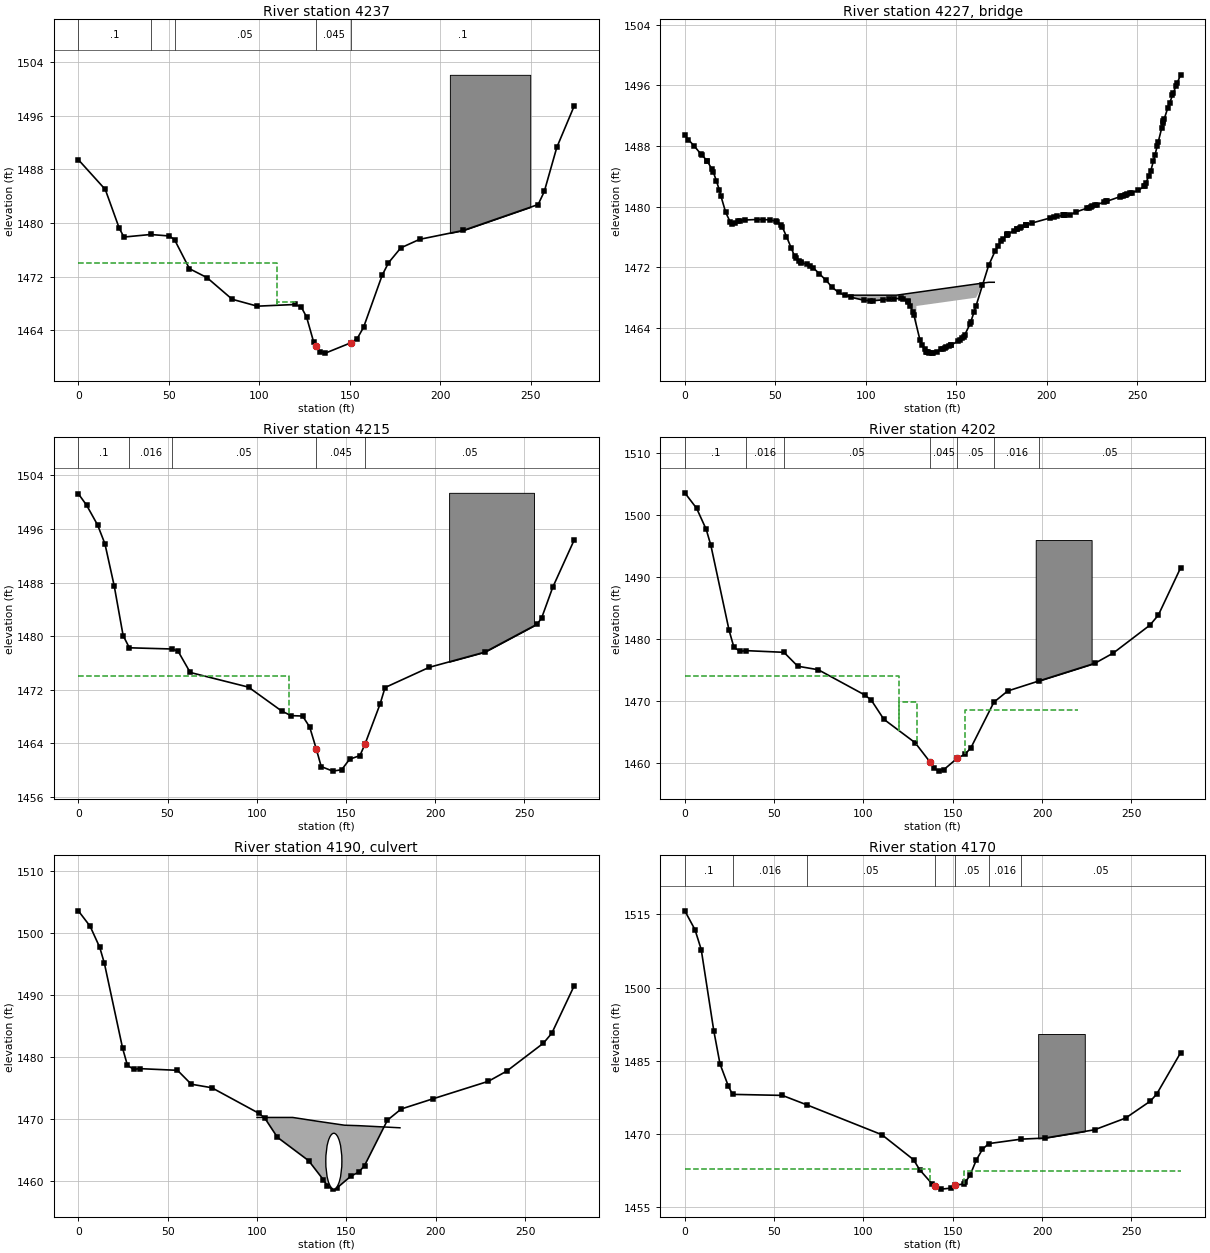
Type RM Length L Ch R = 1 ,4237    ,22,22,21.7
BEGIN DESCRIPTION:
This XS was not surveyed
END DESCRIPTION:
XS GIS Cut Line= 3
1995032.25457451239010.652084313 1995070.8480099238897.619050709
1995118.25747767238750.494569416
#Sta/Elev= 30
       0 1489.43    14.9 1484.99    22.6 1479.23    25.2 1477.91    39.9 1478.29
    50.3 1478.07    53.2  1477.5    61.4  1473.2    71.1 1471.87      85 1468.65
    98.9 1467.62   119.7 1467.87   123.1 1467.53   126.1 1466.03     130 1462.32
   131.3 1461.67   133.5 1460.82   136.5 1460.63   150.7 1462.18   154.1  1462.8
   157.6 1464.46   167.9 1472.22   171.4 1474.08   178.2  1476.3   188.6 1477.57
   212.7 1478.89   254.1 1482.75   257.5  1484.7   264.4 1491.25     274 1497.41
#Mann= 5 ,-1 , 0
       0      .1       0    39.9    .016       0    53.2     .05       0
   131.3    .045       0   150.7      .1       0
#XS Ineff= 3 ,-1
       0     110    1474     110     120 1468.29     170     250 1469.99
Permanent Ineff=
       F       F       F
#Block Obstruct= 1 ,-1
  205.32  249.72 1502.06
Bank Sta=131.3,150.7
XS Rating Curve= 0 ,0
Exp/Cntr(USF)=0,0
Exp/Cntr=0.5,0.3

Type RM Length L Ch R = 3 ,4227    ,,,
BEGIN DESCRIPTION:
Private Drive
Survey ID: BER070
END DESCRIPTION:
Bridge Culvert--1,0,-1,-1, 0
Deck Dist Width WeirC Skew NumUp NumDn MinLoCord MaxHiCord MaxSubmerge Is_Ogee
10,8,2.6,0, 8, 8, , , 0.98, 0, 0,0,,
      90     117     128     128     166     166     168     171
1468.2891468.289 1468.66 1468.66 1469.93 1469.931469.9941469.994
                         1466.86 1468.13
      90     117     128     128     166     166     168     171
1468.2891468.289 1468.66 1468.66 1469.93 1469.931469.9941469.994
                         1466.86 1468.13
BR Coef=-1 , 1 , 0 ,, 0 ,,,0.8,0,1.2,0,
WSPro=,,,, 1 ,,,, 0 ,,,, 0 ,,,,-1 ,-1 ,-1 , 0 , 0 , 0 , 0 , 0
BR U #Sta/Elev= 147
       0 1489.43     1.9 1488.86     5.3 1487.98     8.7 1486.99     9.7 1486.75
    12.2 1486.08    12.5 1485.96    14.9 1484.99    15.7  1484.6    17.5 1483.37
    19.1 1482.17      20 1481.36    22.6 1479.23    25.2 1477.91    26.1 1477.68
    27.8 1477.85    29.5 1478.08    30.4 1478.13      33 1478.22    39.9 1478.29
    43.3 1478.28    46.9 1478.24    50.3 1478.07    51.1 1477.96    53.2  1477.5
    53.8 1477.34    56.2 1476.04    58.8 1474.51    60.7 1473.43    61.4  1473.2
    63.3 1472.76      64 1472.63    64.2  1472.6    67.7 1472.36    69.1 1472.16
    71.1 1471.87    74.3 1471.14    78.1 1470.24    81.5 1469.31      85 1468.65
    88.5 1468.27    91.9 1468.01    98.9 1467.62   102.3 1467.54   103.9 1467.55
   109.3 1467.67   113.1 1467.72   115.7  1467.8   119.7 1467.87   120.8 1467.78
   123.1 1467.53   123.4  1467.4   124.5 1466.88   126.1 1466.03   126.6 1465.66
     130 1462.32   131.3 1461.67   132.6 1461.18   133.5 1460.82   133.9 1460.76
   134.51460.728   135.2 1460.69   136.5 1460.63   136.9 1460.63   139.1 1460.84
   141.7 1461.14   142.8 1461.24   143.8 1461.34   144.3  1461.4   145.9 1461.56
   146.9 1461.67   147.2  1461.7   150.7 1462.18   152.1 1462.42   153.21462.629
   154.1  1462.8   154.7 1463.05   157.6 1464.46   158.1  1464.8   159.9 1466.13
     161 1466.92   164.5 1469.61   167.9 1472.22   171.4 1474.08     173 1474.74
   174.8 1475.44   175.6 1475.67     178 1476.25   178.2  1476.3   178.3 1476.31
   178.4 1476.33   181.7  1476.8   183.4    1477   183.5 1477.01   185.2 1477.21
     186  1477.3   188.6 1477.56   188.6 1477.57   188.7 1477.57   192.1 1477.84
   201.7 1478.48   204.3 1478.63   205.8 1478.72   208.9 1478.82   209.3 1478.84
   209.5 1478.84   210.1 1478.85   212.7 1478.89   216.2 1479.28   222.5 1479.81
   223.1 1479.86   224.2 1479.96   225.1 1480.05   226.5 1480.17   227.7 1480.27
   231.5 1480.56   232.9 1480.67   233.4 1480.71   240.3 1481.29   240.8 1481.33
   242.2 1481.43   243.4 1481.53   243.8 1481.56   244.5 1481.62     246 1481.75
   247.2 1481.85   250.7 1482.14   253.8 1482.67   254.1 1482.75   254.7 1483.09
   256.4 1483.99   257.5  1484.7     259 1486.06   259.8 1486.79     261 1487.94
   261.6 1488.57   263.6 1490.43   264.2 1491.07   264.4 1491.25   264.9 1491.55
   266.8 1492.96   267.9 1493.68   269.4 1494.68   269.9 1494.99   271.3 1495.87
     272 1496.27     274 1497.41
BR U #Mann= 5
       0      .1    39.9    .016    53.2     .05   131.3     .04   150.7      .1
BR D #Sta/Elev= 150
       0 1501.25     1.2 1500.95     2.8 1500.31     4.6 1499.56     5.5 1499.14
     8.1 1497.78     8.4 1497.65    10.8 1496.59    11.5 1496.18    12.7  1495.3
    13.4  1494.9    14.9 1493.79    18.3 1489.88    18.7 1489.36    20.1 1487.52
    22.4 1484.12      24 1481.76    25.1  1480.1    26.6 1479.18    27.2 1478.95
    28.6 1478.27    29.3 1478.19    31.9 1478.09    35.4 1478.12    38.8 1478.19
    45.7 1478.19    49.1 1478.16    52.5 1478.09    55.9 1477.76    59.3 1476.18
      61 1475.35    62.7 1474.59    63.7 1474.48    66.2 1474.32    69.6 1474.29
    71.6 1474.24    74.2 1474.11    76.9 1473.92    79.8 1473.58    82.2 1473.43
    83.2 1473.34    84.8 1473.24    86.7 1473.11      90 1472.82    92.8 1472.65
    94.9 1472.45    95.4  1472.4    96.9 1472.21    98.1 1472.02    99.7 1471.66
   101.9 1471.22   103.8  1470.8   104.5 1470.66     106 1470.43   107.2 1470.19
   108.6 1469.91   109.3 1469.74   110.6 1469.47   113.6  1468.9   113.9 1468.85
     114 1468.84   114.2 1468.81   116.6 1468.52   117.4 1468.38   119.2 1468.15
     120 1468.13   125.7 1468.09  129.67 1466.45  133.35 1463.19  136.13 1460.55
  136.93 1460.39  142.62 1459.87  147.59 1460.08     149 1460.67  152.02 1461.64
  157.84 1462.19  160.73 1463.94  166.53 1468.32  169.12 1469.88  171.91 1472.34
   175.9 1472.66   176.8 1472.84   179.3 1473.27   179.3 1473.28   182.8  1473.8
   186.3 1474.22   196.7 1475.36   197.5 1475.43     200 1475.67   200.1 1475.68
   200.2 1475.69   202.7 1475.92     207 1476.26   207.9 1476.29   210.2 1476.42
   210.4 1476.43   210.5 1476.43   210.6 1476.44     213 1476.51   215.6 1476.62
   220.5 1476.91   220.8 1476.93   220.9 1476.94   224.4 1477.32     226 1477.46
   226.3 1477.49   227.8 1477.62   228.6 1477.72   230.8 1477.97   231.1 1478.02
   231.3 1478.03   233.7 1478.41   234.7 1478.56   236.3 1478.81   236.8 1478.89
   238.2 1479.12   241.5 1479.66   241.7 1479.69     242 1479.74   244.1 1480.07
   245.1 1480.22   246.7 1480.41   247.2 1480.48   248.6 1480.64   251.3 1480.91
   251.9 1480.98   252.1 1481.01   252.5 1481.05   254.4 1481.28   255.5 1481.41
     257 1481.77   257.7 1481.96     259 1482.31   259.6 1482.67   262.4 1484.46
   262.9 1484.85   264.8  1486.4   265.9  1487.3   267.4  1488.2   268.1 1488.61
   269.4 1489.32     270 1489.66   271.8 1490.68   272.6 1491.12   272.8 1491.28
   273.4 1491.62   275.2 1492.75   276.3 1493.48   277.7 1494.28   277.9 1494.34
BR D #Mann= 5
       0      .1    28.6    .016    52.5     .05  133.35     .04  160.73     .05
BC Design=,, 0 ,, 0 ,,,,,,
BC Use User HTab Curves=0
BC User HTab FreeFlow(D)= 0

Type RM Length L Ch R = 1 ,4215    ,12.2,12.9,13.6
BEGIN DESCRIPTION:
Channel burned from survey ID: 54089BER068BD
END DESCRIPTION:
XS GIS Cut Line= 4
1995056.92589617 239023.241788811995090.69064166238907.725428968
1995104.50168776238863.1575063921995139.96260411238758.117621437
#Sta/Elev= 30
       0 1501.25     4.6 1499.56    10.8 1496.59    14.9 1493.79    20.1 1487.52
    25.1  1480.1    28.6 1478.27    52.5 1478.09    55.9 1477.76    62.7 1474.59
    95.4  1472.4   113.9 1468.85   119.2 1468.15   125.7 1468.09  129.67 1466.45
  133.35 1463.19  136.13 1460.55  142.62 1459.87  147.59 1460.08  152.02 1461.64
  157.84 1462.19  160.73 1463.94  169.12 1469.88  171.91 1472.34   196.7 1475.36
   227.8 1477.62     257 1481.77   259.6 1482.67   265.9  1487.3   277.9 1494.34
#Mann= 5 ,-1 , 0
       0      .1       0    28.6    .016       0    52.5     .05       0
  133.35    .045       0  160.73     .05       0
#XS Ineff= 3 ,-1
       0     118    1474     118     123 1468.06     171     220  1469.6
Permanent Ineff=
       F       F       F
#Block Obstruct= 1 ,-1
  207.81  255.37 1501.39
Bank Sta=133.35,160.73
XS Rating Curve= 0 ,0
Exp/Cntr(USF)=0,0
Exp/Cntr=0.5,0.3

Type RM Length L Ch R = 1 ,4202    ,32.2,31.8,31.7
BEGIN DESCRIPTION:
Channel Invert determined by BER062CU
END DESCRIPTION:
XS GIS Cut Line= 4
1995059.86561469239024.9827128981995102.01158623238909.776768837
1995117.22873473238869.6762377661995154.69812226238764.204366442
#Sta/Elev= 30
       0 1503.61     6.6 1501.12      12  1497.7    14.6 1495.12    24.8 1481.42
    27.5 1478.67      31 1478.05    34.5 1478.15    55.5 1477.88    63.2 1475.64
    74.7 1475.07   100.9 1470.97   104.4 1470.15   111.4 1467.08   128.9  1463.3
   137.1 1460.24   139.4 1459.21   142.31458.714  144.91 1458.94   152.6 1460.82
     157 1461.46   160.2 1462.52     173 1469.84   180.7 1471.64   198.3 1473.27
   229.5 1476.11   239.8 1477.76   260.3 1482.26     265 1483.87   277.5 1491.51
#Mann= 7 ,-1 , 0
       0      .1       0    34.5    .016       0    55.5     .05       0
   137.1    .045       0   152.6     .05       0     173    .016       0
   198.3     .05       0
#XS Ineff= 3 ,-1
       0     120    1474     120     130 1469.86     157     220 1468.61
Permanent Ineff=
       F       F       F
#Block Obstruct= 1 ,-1
   196.4  227.68 1495.99
Bank Sta=137.1,152.6
XS Rating Curve= 0 ,0
Exp/Cntr(USF)=0,0
Exp/Cntr=0.5,0.3

Type RM Length L Ch R = 2 ,4190    ,,,
BEGIN DESCRIPTION:
Private Driveway
Survey ID:BER060
END DESCRIPTION:
Bridge Culvert--1,0,-1,-1, 0
Deck Dist Width WeirC Skew NumUp NumDn MinLoCord MaxHiCord MaxSubmerge Is_Ogee
7,17,2.6,0, 6, 6, , , 0.98, 0, 0,0,,
     100     120     134     149     157     180
1470.2781470.2781469.6581469.0271468.9511468.609
                                                
     100     120     134     149     157     180
1470.2781470.2781469.6581469.0271468.9511468.609
                                                
BR Coef=-1 , 1 , 0 ,, 0 ,,,0.8,0,1.2,0,
WSPro=,,,, 1 ,,,, 0 ,,,, 0 ,,,,-1 ,-1 ,-1 , 0 , 0 , 0 , 0 , 0
Culvert=1,9,,17,0.012,0.2,1,55,1,1458.728,143,1458.733,147,Culvert #1  , 0 ,12
     143     147
BC Culvert Barrel=1,Barrel1,0
Culvert Bottom n=0.012
BC Design=,, 0 ,, 0 ,,,,,,
BC Use User HTab Curves=0
BC User HTab FreeFlow(D)= 0

Type RM Length L Ch R = 1 ,4170    ,151.3,149.4,147.7
BEGIN DESCRIPTION:
Channel Invert determined by BER058CD
END DESCRIPTION:
XS GIS Cut Line= 4
1995090.28636111 239033.984770511995132.43233265238918.778826449
1995147.64948114238878.6782953791995185.11886868238773.206424055
#Sta/Elev= 30
       0 1515.75     5.7 1511.89     9.2  1507.8    16.2 1491.22    19.7 1484.38
    24.3 1479.89    26.7 1478.13    54.6 1477.92    68.6 1475.94   110.3 1469.86
     128 1464.75   131.5 1462.66   138.4 1459.79     1401459.433  143.54 1458.71
  149.03 1458.92   151.2 1459.52   156.1 1459.76   156.9 1460.11   159.6 1461.51
   163.1 1464.64   166.6 1466.88   170.1 1468.04   188.4 1468.96   201.4 1469.17
   229.3 1470.87   246.7 1473.27   260.6 1476.76   264.1 1478.19   277.5 1486.67
#Mann= 7 ,-1 , 0
       0      .1       0    26.7    .016       0    68.6     .05       0
     140    .045       0   151.2     .05       0   170.1    .016       0
   188.4     .05       0
#XS Ineff= 2 , 0
             137  1462.9     156          1462.4
Permanent Ineff=
       F       F
#Block Obstruct= 1 ,-1
  197.76  223.86 1490.51
Bank Sta=140,151.2
XS Rating Curve= 0 ,0
Exp/Cntr(USF)=0,0
Exp/Cntr=0.5,0.3