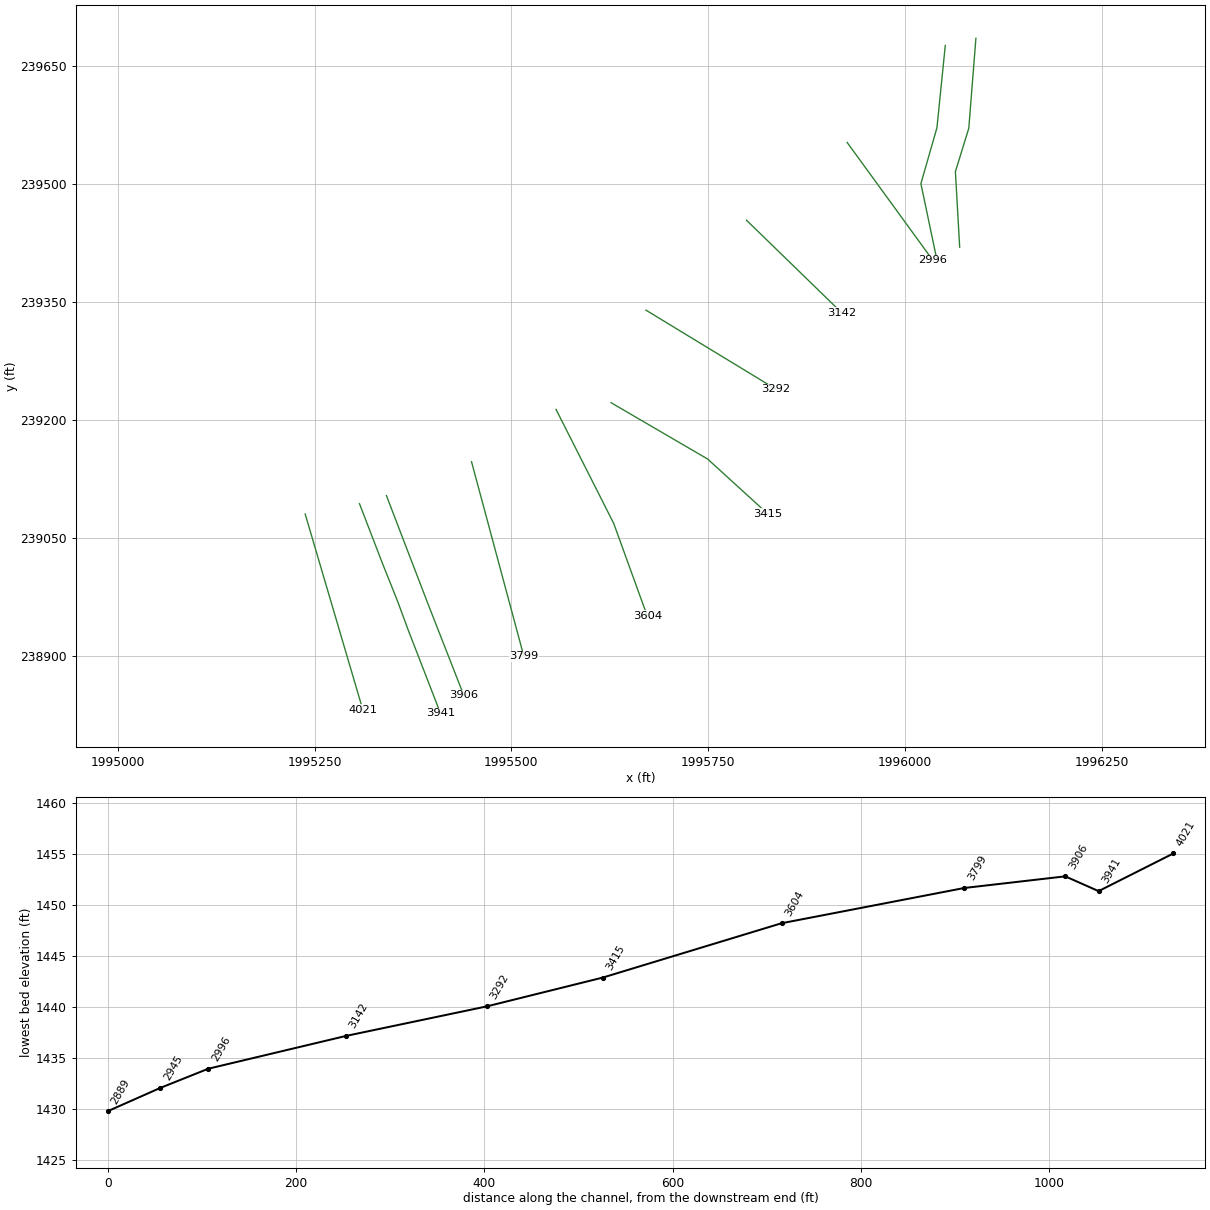
HEC-RAS study BEECHRN.prj: BEECHRN

--- BEECHRN.g01 (geometry) --- (continued)

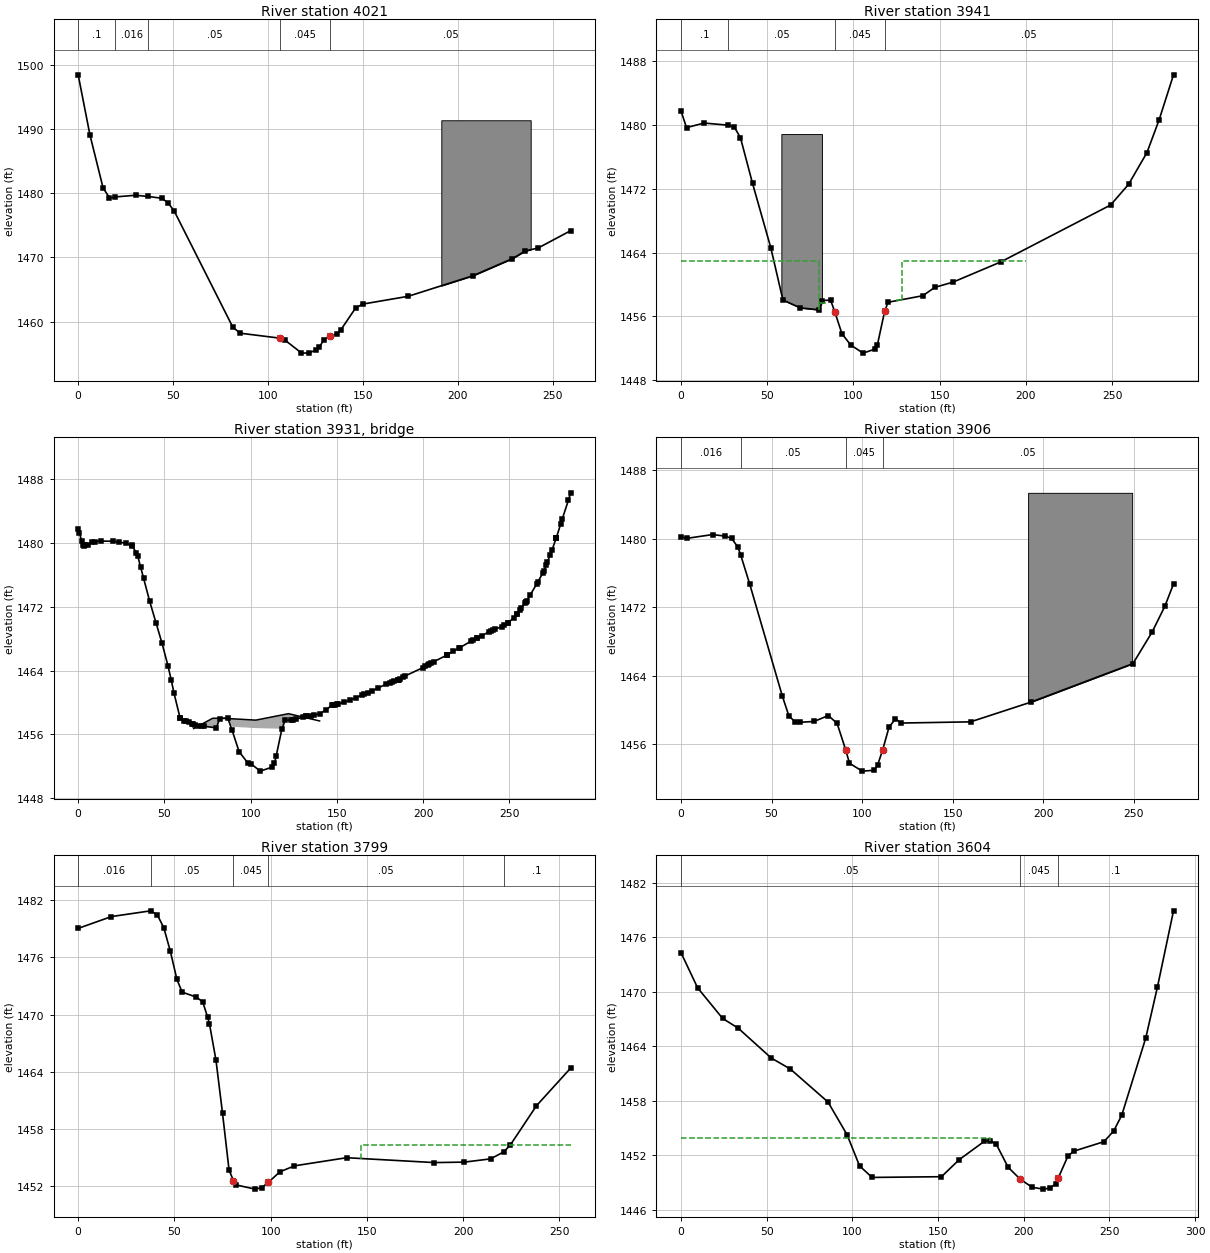
Type RM Length L Ch R = 1 ,4021    ,78,79.5,80.6
XS GIS Cut Line= 2
1995238.13935025239080.5631348631995311.42448686238831.734531506
#Sta/Elev= 30
       0  1498.4     6.2 1489.05    13.1 1480.83    16.5 1479.25    19.3  1479.4
    30.2 1479.66      37 1479.47    43.9  1479.2    47.3 1478.52    50.7 1477.14
    81.5 1459.11    85.4  1458.2   106.5 1457.42   108.9 1457.13  117.61 1455.12
   121.4  1455.1  125.01 1455.56  127.07 1456.04   129.4 1457.19   132.8 1457.75
   136.2 1458.11   138.2 1458.66   146.1 1462.11   149.9 1462.73   173.8 1463.94
     208 1467.15   228.6 1469.79   235.4 1470.99   242.2 1471.45   259.4 1474.15
#Mann= 5 ,-1 , 0
       0      .1       0    19.3    .016       0      37     .05       0
   106.5    .045       0   132.8     .05       0
#Block Obstruct= 1 ,-1
  191.26  238.34 1491.33
Bank Sta=106.5,132.8
XS Rating Curve= 0 ,0
Exp/Cntr(USF)=0,0
Exp/Cntr=0.5,0.3

Type RM Length L Ch R = 1 ,3941    ,35.4,35.4,35.1
BEGIN DESCRIPTION:
Channel burned from survey ID: 54089BER052BU
END DESCRIPTION:
XS GIS Cut Line= 5
1995307.14618483239093.6498177311995336.62563837239017.105591276
1995355.28048768238970.4885515231995368.53958729 238934.49956685
1995410.07109422238827.297365591
#Sta/Elev= 30
       0 1481.73     3.2 1479.65    13.4 1480.22    27.5 1479.95      31 1479.69
    34.5 1478.37    41.5 1472.65    52.1 1464.58    59.1 1458.05    69.2 1457.07
    80.2 1456.82      82 1457.98   86.75 1458.05   89.25 1456.52   93.34 1453.83
   98.41 1452.42   105.6  1451.4   112.3 1451.89  113.82 1452.36  118.08 1456.63
  120.04 1457.77   140.2 1458.59   147.2 1459.64   157.7 1460.29   185.4 1462.82
   249.1 1469.95   259.5 1472.53   270.2 1476.52   277.3 1480.65   285.6 1486.26
#Mann= 4 ,-1 , 0
       0      .1       0    27.5     .05       0   89.25    .045       0
  118.08     .05       0
#XS Ineff= 4 ,-1
       0      80    1463      80      85  1457.7     125     128  1458.1
     128     200    1463
Permanent Ineff=
       F       F       F       F
#Block Obstruct= 1 ,-1
    58.2   81.73 1478.84
Bank Sta=89.25,118.08
XS Rating Curve= 0 ,0
Exp/Cntr(USF)=0,0
Exp/Cntr=0.5,0.3

Type RM Length L Ch R = 3 ,3931    ,,,
BEGIN DESCRIPTION:
Private Drive
Survey ID: BER050
END DESCRIPTION:
Bridge Culvert--1,0,-1,-1, 0
Deck Dist Width WeirC Skew NumUp NumDn MinLoCord MaxHiCord MaxSubmerge Is_Ogee
14,11,2.6,0, 8, 8, , , 0.98, 0, 0,0,,
      67      78      84      84     103     122     122     140
1456.7341458.0221458.0221458.0221457.7891458.5981458.5981457.684
                        1457.0221456.7891456.684
      67      78      84      84     103     122     122     140
1456.7341458.0221458.0221458.0221457.7891458.5981458.5981457.684
                        1457.1221456.8891456.784
BR Coef=-1 , 1 , 0 ,, 0 ,,,0.8,-1,1.2,0,
WSPro=,,,, 1 ,,,, 0 ,,,, 0 ,,,,-1 ,-1 ,-1 , 0 , 0 , 0 , 0 , 0
BR U #Sta/Elev= 133
       0 1481.73      .7 1481.19     2.1 1480.25     2.9  1479.7     3.2 1479.65
     4.1 1479.68     5.7 1479.77     8.3 1480.04     9.9 1480.16    13.4 1480.22
    20.4 1480.19    23.5  1480.1    27.5 1479.95      31 1479.69    31.5 1479.54
    33.7 1478.76    34.5 1478.37    36.2 1476.99      38 1475.55    41.5 1472.65
    45.1 1470.01    48.6 1467.44    52.1 1464.58      54 1462.78    55.6 1461.15
    59.1 1458.05    59.3 1458.03    61.6 1457.74    62.6 1457.64    64.1  1457.5
    66.2 1457.35    66.7 1457.28      68 1457.17    69.2 1457.07    71.7 1457.03
    73.2 1457.01    80.2 1456.82      82 1457.98   86.75 1458.05   89.25 1456.52
   93.34 1453.83   98.41 1452.42   100.5 1452.27   105.6  1451.4   112.3 1451.89
  113.82 1452.36  114.83  1453.3  118.08 1456.63  120.04 1457.77  123.66 1457.78
   124.8 1457.84   126.1 1457.92   130.3 1458.14   132.2 1458.25   132.4 1458.26
   134.9 1458.35   136.7 1458.41   140.2 1458.59   143.7 1459.09   147.2 1459.64
   147.7 1459.67   149.1 1459.74   150.3  1459.8   150.7 1459.82   154.2 1460.03
   157.7 1460.29   161.2 1460.61   164.7 1460.95   165.6 1461.04   168.1 1461.24
   170.6 1461.48   173.9  1461.8   178.7 1462.32   180.8 1462.46   182.2 1462.56
   183.4 1462.65   185.4 1462.82   185.7 1462.85   185.9 1462.87   186.4 1462.93
   188.4  1463.2   189.3 1463.29   199.8 1464.35   201.1 1464.51   202.6 1464.68
   203.7 1464.81   204.5 1464.91   206.2 1465.11   213.8 1465.92   213.9 1465.93
   214.1 1465.96   217.4  1466.4   220.9 1466.81   221.4 1466.88     228 1467.71
     229 1467.82   231.3 1468.05   231.5 1468.07   234.1 1468.38   238.5 1468.88
   239.2 1468.95   240.8  1469.1   241.7 1469.17   245.6  1469.5   246.8 1469.66
   249.1 1469.95   249.3 1469.99   252.6  1470.6   254.3 1471.07   254.4  1471.1
   256.1 1471.57   256.9  1471.8     259 1472.41   259.5 1472.53   259.6 1472.59
     260 1472.73     262 1473.41   265.8 1474.81   266.7 1475.15   269.6 1476.27
   270.2 1476.52   271.5 1477.24   272.1 1477.58   273.7 1478.44   274.7 1479.05
   277.2  1480.6   277.2 1480.62   277.2 1480.63   277.3 1480.65   279.7 1482.31
   280.7 1482.97   284.3 1485.35   285.6 1486.26
BR U #Mann= 4
       0      .1    27.5     .05   89.25     .03  118.08     .05
BR D #Sta/Elev= 118
       0 1480.24     2.4 1480.07     3.3 1480.06       5 1480.19     6.9 1480.31
    10.4 1480.41    17.4  1480.5    20.9 1480.44    24.4 1480.32    27.9 1480.06
    30.4  1479.4    31.4 1479.05    32.9 1478.16      35 1476.83    36.8 1475.54
      38 1474.68    40.5 1472.82      42 1471.71    43.1 1470.93    45.5 1469.27
    45.6 1469.19    45.9 1468.97    48.2 1467.27      49 1466.63    52.5  1464.2
    55.1 1462.33      56  1461.6    56.6 1461.21    58.3 1460.04    59.6  1459.3
    60.9 1458.97    62.3 1458.75    63.1  1458.6    63.4 1458.59    65.9 1458.56
    70.1 1458.57    73.6 1458.66      76 1458.88   81.36 1459.35   86.21 1458.43
   90.91 1455.37   93.05 1453.77  100.11 1452.85   106.8 1452.95  108.63 1453.59
  111.38 1455.33  114.88 1457.98  118.45 1458.97  121.51 1458.47   159.9 1458.61
   161.5 1458.77   164.9 1458.99   168.6 1459.12   172.1 1459.34   179.1 1459.89
   180.1 1459.97   182.6 1460.19   182.7 1460.19   185.2 1460.37   186.2 1460.44
   187.7 1460.55   189.7 1460.68   190.2 1460.71   191.6  1460.8   192.8 1460.88
   193.2 1460.91   195.3  1461.1   196.7 1461.22   200.4 1461.52   200.6 1461.54
   202.9 1461.72   205.4 1461.92   207.3 1462.08     208 1462.12   209.6 1462.24
   210.5  1462.3   210.8 1462.32   211.6 1462.37     213 1462.46   215.6 1462.65
   217.9  1462.8   218.1 1462.81   218.6 1462.85   220.6 1463.01   221.4 1463.09
   223.2 1463.24   224.9 1463.38   225.7 1463.43   227.6 1463.55   228.2 1463.59
   228.5  1463.6     239 1464.61   242.5  1464.9   243.4 1464.94   245.9 1465.08
   246.1 1465.09   246.4 1465.12   249.6 1465.42     251 1465.89   252.1 1466.27
   253.1 1466.59   253.5 1466.72   254.6 1467.06   256.1 1467.52   256.6 1467.71
   257.9 1468.22   258.6 1468.49   260.2 1469.11   261.1 1469.52   263.6 1470.57
   263.7 1470.59   263.7 1470.61   267.2 1472.11   268.7 1472.87   269.5 1473.29
   270.7 1473.92   271.3 1474.26     272 1474.73
BR D #Mann= 4
       0    .016    32.9     .05   90.91     .03  111.38     .05
BC Design=,, 0 ,, 0 ,,,,,,
BC Use User HTab Curves=0
BC User HTab FreeFlow(D)= 0

Type RM Length L Ch R = 1 ,3906    ,109.3,107.1,106.8
BEGIN DESCRIPTION:
Channel burned from survey ID: 54089BER048BD
END DESCRIPTION:
XS GIS Cut Line= 4
1995341.38997577239103.9329338061995368.28375456239033.799443599
1995394.26270824238966.1724122671995439.61122876238850.321778199
#Sta/Elev= 30
       0 1480.24     3.3 1480.06    17.4  1480.5    24.4 1480.32    27.9 1480.06
    31.4 1479.05    32.9 1478.16      38 1474.68      56  1461.6    59.6  1459.3
    63.1  1458.6    65.9 1458.56    73.6 1458.66   81.36 1459.35   86.21 1458.43
   90.91 1455.37   93.05 1453.77  100.11 1452.85   106.8 1452.95  108.63 1453.59
  111.38 1455.33  114.88 1457.98  118.45 1458.97  121.51 1458.47   159.9 1458.61
   193.2 1460.91   249.6 1465.42   260.2 1469.11   267.2 1472.11     272 1474.73
#Mann= 4 ,-1 , 0
       0    .016       0    32.9     .05       0   90.91    .045       0
  111.38     .05       0
#XS Ineff= 2 , 0
        81.66666  1456.3128.3333          1456.3
Permanent Ineff=
       F       F
#Block Obstruct= 1 ,-1
   191.7  249.15 1485.38
Bank Sta=90.91,111.38
XS Rating Curve= 0 ,0
Exp/Cntr(USF)=0,0
Exp/Cntr=0.5,0.3

Type RM Length L Ch R = 1 ,3799    ,194.2,194.2,196.4
XS GIS Cut Line= 2
1995449.47323255239147.0310494581995515.94114715238899.906751603
#Sta/Elev= 30
       0 1479.02    17.3 1480.26    37.7 1480.86    41.1 1480.45    44.5 1479.08
    47.9 1476.62    51.3 1473.68      54 1472.35    61.4 1471.82    64.7 1471.33
    67.3  1469.7    68.2 1469.04    71.6 1465.22      75 1459.66    78.4 1453.71
    80.7 1452.58    81.8 1452.16      92 1451.71    95.4 1451.87    98.8 1452.42
   104.8 1453.52   112.4 1454.15   139.5    1455   185.1 1454.49   200.7 1454.54
   214.3 1454.88   221.1 1455.61   224.5 1456.32   238.1 1460.44   255.9 1464.39
#Mann= 5 ,-1 , 0
       0    .016       0    37.7     .05       0    80.7    .045       0
    98.8     .05       0   221.1      .1       0
#XS Ineff= 2 , 0
                          147.04         1456.38
Permanent Ineff=
       F       F
Bank Sta=80.7,98.8
XS Rating Curve= 0 ,0
Exp/Cntr(USF)=0,0
Exp/Cntr=0.3,0.1

Type RM Length L Ch R = 1 ,3604    ,177,189.9,196
XS GIS Cut Line= 3
1995556.84447921239213.4989640531995630.12961581239068.632996345
1995672.73725338238951.035916677
#Sta/Elev= 30
       0 1474.32     9.7 1470.44    24.3 1467.07    33.4 1465.99    52.7  1462.7
    63.8 1461.49    85.8 1457.85    96.9 1454.25   104.2 1450.81   111.5 1449.54
     152 1449.62   162.3 1451.49     177 1453.52   180.5 1453.61     184 1453.19
   190.9 1450.66   197.9 1449.36   204.9 1448.45   211.5 1448.25   215.4 1448.36
   218.8 1448.87   220.2  1449.5   225.8  1451.9   229.3 1452.44   246.8 1453.48
   252.5 1454.66   257.2  1456.4   271.2 1464.91     278 1470.51   287.4 1478.93
#Mann= 3 ,-1 , 0
       0     .05       0   197.9    .045       0   220.2      .1       0
#XS Ineff= 2 , 0
          180.34 1453.84
Permanent Ineff=
       F       F
Bank Sta=197.9,220.2
XS Rating Curve= 0 ,0
Exp/Cntr(USF)=0,0
Exp/Cntr=0.3,0.1

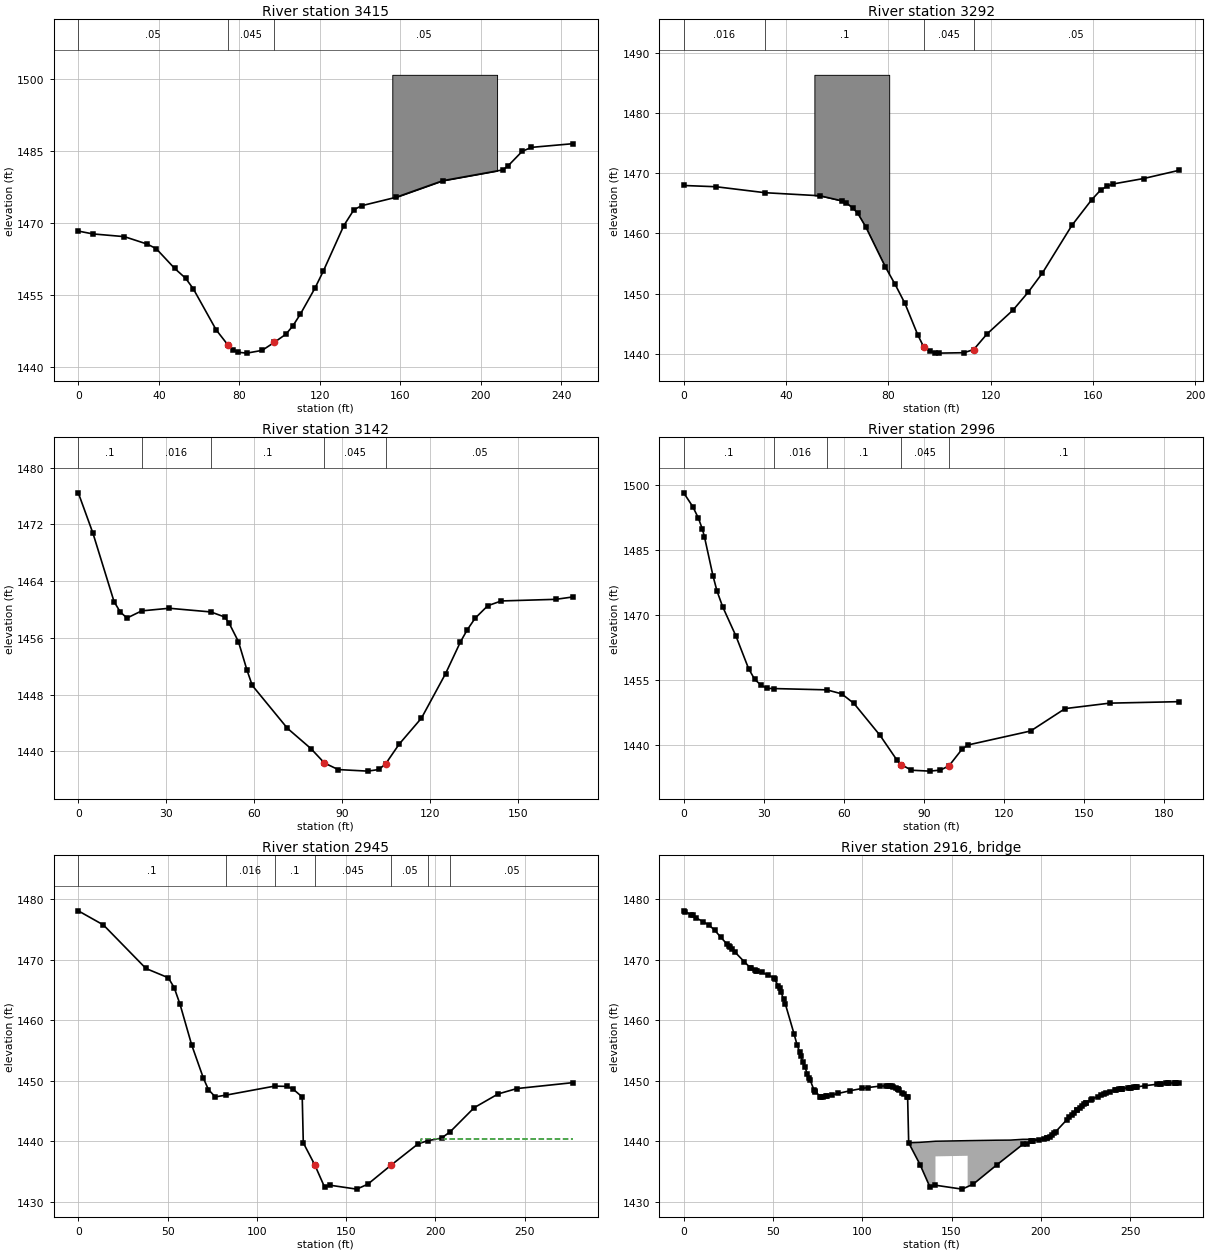
Type RM Length L Ch R = 1 ,3415    ,123,122.9,122.6
Node Name=A
XS GIS Cut Line= 3
1995626.72100481239222.0204915651995749.43100098239150.439660463
 1995826.1247486239080.563134863
#Sta/Elev= 30
       0 1468.31     7.2 1467.72    22.9 1467.15    34.3 1465.59    38.7 1464.65
    47.9 1460.53    53.3  1458.5    57.1 1456.32    68.5 1447.75    74.3 1444.63
    76.7 1443.65    79.1 1443.11    83.7 1442.92    91.3 1443.49    97.3 1445.14
   103.1 1446.85   106.5 1448.53   110.3 1451.02   117.5 1456.39   121.7 1459.97
   131.9 1469.45   136.9 1472.74   140.7 1473.58   157.8 1475.33     181 1478.78
   210.9 1481.04   213.5 1481.88   220.5  1484.9   225.1 1485.72   245.8 1486.49
#Mann= 3 ,-1 , 0
       0     .05       0    74.3    .045       0    97.3     .05       0
#Block Obstruct= 1 ,-1
  155.97  208.02 1500.81
Bank Sta=74.3,97.3
XS Rating Curve= 0 ,0
Exp/Cntr(USF)=0,0
Exp/Cntr=0.3,0.1

Type RM Length L Ch R = 1 ,3292    ,152.4,149.6,146.9
XS GIS Cut Line= 2
1995671.03294787239339.6175712341995836.35058161 239239.06354659
#Sta/Elev= 30
       0 1467.96    12.7 1467.75    31.8 1466.76    53.3 1466.25    61.8 1465.41
    63.5 1465.09    66.2  1464.2    68.1 1463.31    71.2 1461.07    78.9 1454.39
    82.7 1451.51    86.5 1448.38    91.5 1443.17    93.9 1441.09    96.3 1440.43
    98.1 1440.16    99.7  1440.1   109.6 1440.17   113.4 1440.69   118.6 1443.28
   128.8 1447.26   134.8 1450.27   140.3 1453.43   151.8 1461.33   159.5 1465.57
   163.1 1467.23   165.5 1467.82   167.9 1468.21   179.9 1469.12   193.5 1470.46
#Mann= 4 ,-1 , 0
       0    .016       0    31.8      .1       0    93.9    .045       0
   113.4     .05       0
#Block Obstruct= 1 ,-1
   51.11   80.36 1486.35
Bank Sta=93.9,113.4
XS Rating Curve= 0 ,0
Exp/Cntr(USF)=0,0
Exp/Cntr=0.3,0.1

Type RM Length L Ch R = 1 ,3142    ,148.3,146.4,143.7
XS GIS Cut Line= 2
1995798.85586056239453.8060398981995919.86155123239336.208960229
#Sta/Elev= 30
       0 1476.45       5 1470.75    12.2  1461.1    14.3 1459.65    16.6 1458.79
    21.6  1459.8      31 1460.17    45.2 1459.65    49.9 1458.94    51.4 1458.08
    54.6 1455.46    57.5 1451.46    59.3 1449.29    71.3 1443.24    79.3 1440.38
    83.9 1438.35    88.6 1437.42    98.7  1437.2   102.5 1437.43   104.8 1438.24
   109.4 1441.01     117 1444.68   125.2 1450.94   130.3 1455.44   132.6 1457.13
   135.3 1458.77   139.6 1460.53   144.2  1461.2   162.8 1461.43   168.7 1461.77
#Mann= 5 ,-1 , 0
       0      .1       0    21.6    .016       0    45.2      .1       0
    83.9    .045       0   104.8     .05       0
Bank Sta=83.9,104.8
XS Rating Curve= 0 ,0
Exp/Cntr(USF)=0,0
Exp/Cntr=0.3,0.1

Type RM Length L Ch R = 1 ,2996    ,63.5,50.9,42.9
XS GIS Cut Line= 2
1995926.67877324 239552.65575904 1996035.7543254239402.676874825
#Sta/Elev= 30
       0 1498.25     3.4 1495.07     5.5 1492.43       7 1489.87     7.8 1488.04
      11 1479.03    12.5 1475.54    14.6 1471.95    19.6 1465.15    24.3 1457.68
    26.6 1455.17      29 1453.82    31.3 1453.09    33.7 1453.05    53.6 1452.75
    59.2 1451.83    63.8 1449.61    73.6 1442.21      80 1436.44    81.5  1435.5
    85.3 1434.19    92.2 1433.98    96.2 1434.22    99.4  1435.2   104.3 1439.05
   106.5 1440.02     130 1443.25   142.9 1448.42   159.6 1449.68   185.4 1450.02
#Mann= 5 ,-1 , 0
       0      .1       0    33.7    .016       0    53.6      .1       0
    81.5    .045       0    99.4      .1       0
Bank Sta=81.5,99.4
XS Rating Curve= 0 ,0
Exp/Cntr(USF)=0,0
Exp/Cntr=0.5,0.3

Type RM Length L Ch R = 1 ,2945    ,53.5,56,51.7
BEGIN DESCRIPTION:
Channel burned from survey ID: 54089BER042BU
END DESCRIPTION:
XS GIS Cut Line= 4
1996051.37961595239675.8484680381996040.78816383239571.403044531
1996020.40090331239500.2484697171996040.55483671239404.263705123
#Sta/Elev= 30
       0 1478.09    14.1 1475.75    37.9 1468.56    50.4 1467.03    53.7  1465.4
      57 1462.62    63.5 1455.93    70.1  1450.4    72.9 1448.54    76.7 1447.34
    82.8 1447.64   109.9 1449.12   116.7 1449.08   120.1 1448.67   125.4 1447.33
     126 1439.75  132.34 1436.16  137.97  1432.4  140.86 1432.75  155.89  1432.1
   162.1 1432.91  175.27 1436.09  190.27 1439.58   195.7  1440.1   203.4 1440.53
   208.3 1441.59   221.7 1445.56   235.1 1447.83   245.6 1448.72   277.1  1449.7
#Mann= 7 ,-1 , 0
       0      .1       0    82.8    .016       0   109.9      .1       0
  132.34    .045       0  175.27     .05       0   195.7    .016       0
   208.3     .05       0
#XS Ineff= 2 , 0
             120 1439.76     192         1440.34
Permanent Ineff=
       F       F
Bank Sta=132.34,175.27
XS Rating Curve= 0 ,0
Exp/Cntr(USF)=0,0
Exp/Cntr=0.5,0.3

Type RM Length L Ch R = 3 ,2916    ,,,
BEGIN DESCRIPTION:
Rocky Mountain Way
Survey ID: BER040
END DESCRIPTION:
Bridge Culvert--1,0,-1,-1, 0
Deck Dist Width WeirC Skew NumUp NumDn MinLoCord MaxHiCord MaxSubmerge Is_Ogee
11,20,2.6,0, 10, 10, , , 0.98, 0, 0,0,,
     126     132     141     141     159     159     175     183     190     200
1439.7571439.8241440.0141440.0141440.1111440.1111440.1841440.2041440.3361440.336
                        1437.5141437.611
     126     132     141     141     159     159     175     183     190     200
1439.7571439.8241440.0141440.0141440.1111440.1111440.1841440.2041440.3361440.336
                        1437.5141437.611
BR Coef=-1 , 1 , 0 ,, 0 ,,,0.8,0,1.2,0,
WSPro=,,,, 1 ,,,, 0 ,,,, 0 ,,,,-1 ,-1 ,-1 , 0 , 0 , 0 , 0 , 0
BR U #Sta/Elev= 126
       0 1478.09      .9 1477.94     4.2 1477.46       5 1477.33     6.9 1476.93
      11 1476.27    14.1 1475.75    17.4 1474.88    20.7 1473.75      24 1472.67
    25.2 1472.33    25.9 1472.11    27.3 1471.76    28.9 1471.22    33.9 1469.68
    37.2 1468.72    37.9 1468.56    39.9 1468.26    40.5 1468.15    40.9  1468.1
    43.8  1467.9    47.1  1467.5    50.4 1467.03    50.9 1466.77    52.9 1465.74
    53.7  1465.4    54.6 1464.64    55.9 1463.47      57 1462.62    61.9 1457.66
    63.5 1455.93    64.9  1454.8    65.6 1454.12    66.8 1453.04    67.9 1452.27
    69.3 1451.07    70.1  1450.4    70.9 1450.06    72.9 1448.54    73.4 1448.28
    73.8 1448.22    76.6 1447.36    76.7 1447.34    77.9 1447.36    79.8 1447.43
      80 1447.41    82.8 1447.64    86.6 1447.92    93.2 1448.36    99.8 1448.73
   103.1 1448.89   109.9 1449.12   113.3 1449.16   114.5 1449.09   115.8  1449.1
   116.7 1449.08   117.2 1448.98   118.9 1448.81   119.8 1448.68   120.1 1448.67
   120.6 1448.55   122.5 1447.98   123.5  1447.8   125.1 1447.38   125.4 1447.33
     126 1439.75  132.34 1436.16  137.97  1432.4  140.86 1432.75  155.89  1432.1
   162.1 1432.91  175.27 1436.09  190.27 1439.58   192.3 1439.63   194.7 1440.01
   195.1 1440.06   195.7  1440.1   198.9 1440.25   201.6 1440.36   203.2 1440.52
   203.4 1440.53     205 1440.73   206.1 1440.99   207.4 1441.36   208.3 1441.59
   214.5 1443.55   215.9 1443.99   217.2 1444.38   218.4 1444.71     220 1445.13
   220.2 1445.17   221.7 1445.56   222.8  1445.8   224.4 1446.15   225.1 1446.31
   225.5 1446.39   228.3 1446.91   228.4 1446.93   231.8  1447.4   233.8 1447.66
   235.1 1447.83   236.6 1447.99   238.5  1448.2   241.8 1448.48   242.2  1448.5
   243.6  1448.6   244.9 1448.68   245.2  1448.7   245.6 1448.72   248.6 1448.85
   249.9 1448.88   250.5 1448.89   251.9 1448.92   253.2 1448.97   254.1 1449.01
   258.6  1449.2   265.3 1449.44   266.8 1449.49   267.1 1449.49   269.9 1449.57
   271.1  1449.6     272 1449.63   275.3 1449.63   275.4 1449.63   275.6 1449.63
   277.1  1449.7
BR U #Mann= 7
       0      .1    82.8    .016   109.9      .1  132.34     .04  175.27     .05
   195.7    .016   208.3     .05
BR D #Sta/Elev= 134
       0 1459.91     3.4 1459.17     6.7  1458.7       7 1458.63    13.3 1457.48
    17.1 1455.02    19.2 1453.86    19.9 1453.41    20.7    1453    22.2 1452.35
    24.2 1451.31    25.3 1450.86    26.4 1450.25    27.8 1449.61    28.3 1449.42
    29.7 1448.75    31.4 1448.16      33 1447.53    36.3 1446.54    37.5 1446.27
    38.5 1445.98    39.6 1445.72    40.5 1445.56    42.1 1445.17    42.9 1445.02
    43.6 1444.99    46.2 1444.79    49.5 1444.87    52.7 1445.03    55.8  1445.2
    59.4 1445.46    64.9 1445.79    72.5 1446.27    75.8 1446.44    77.1 1446.45
    77.8 1446.47    79.1 1446.49    80.2 1446.32    81.4 1446.29    82.4 1446.16
    83.2 1445.85      85 1445.48    85.7 1445.23      89  1443.7    89.3 1443.57
    92.3 1441.99    92.4 1441.97    95.7 1440.93    98.5 1440.47    98.8 1440.38
    99.3 1440.32   101.5 1440.17   102.1 1440.08   102.9 1440.02   104.6 1439.92
   105.4 1439.84   106.4 1439.81   107.6 1439.79   108.7 1439.74   114.6  1439.6
   115.3 1439.59   118.8 1439.54   122.2 1439.44   124.3 1439.35   125.6 1439.33
     127 1439.16   128.1  1439.1   129.1 1439.01   129.6 1438.79     130 1439.46
  134.58 1439.56  139.94 1435.12  146.11 1430.45  153.77 1430.43  160.99 1429.81
  163.77 1434.78  166.71 1440.18  173.45  1440.2   180.2  1440.3   181.8 1440.31
   181.9 1440.31   183.5 1440.33     185 1440.32   185.2 1440.32   188.7  1440.3
   190.1 1440.29   193.4 1440.33   196.6 1440.51   197.5 1440.58   199.2 1440.74
   199.9  1440.8   200.6 1440.87   203.2 1441.17   206.5 1441.48   209.6 1441.73
   209.8 1441.74     213 1442.12   213.1 1442.13   216.1 1442.68   216.4 1442.71
   216.6 1442.74   219.3 1443.14   219.6 1443.18   220.1 1443.23   222.9 1443.51
   223.6  1443.6   225.5 1443.82   226.2 1443.92   227.1 1444.03   228.6 1444.22
   229.5 1444.34   230.5 1444.46   231.7 1444.58   232.8 1444.71   234.8 1444.95
   236.1 1445.11   237.5 1445.28   237.9 1445.33   239.4  1445.5     241 1445.72
   242.6 1445.94   245.9 1446.31   247.2 1446.47     248 1446.56   249.2 1446.72
   259.1 1447.64   259.7 1447.68   261.9 1447.82   262.4 1447.85   262.8 1447.87
   265.4 1447.99   265.7 1448.01   265.9 1448.02   268.4 1448.11
BR D #Mann= 5
       0      .1    64.9    .016   128.1     .05  139.94     .04  163.77     .05
BC Design=,, 0 ,, 0 ,,,,,,
BC Use User HTab Curves=0
BC User HTab FreeFlow(D)= 0

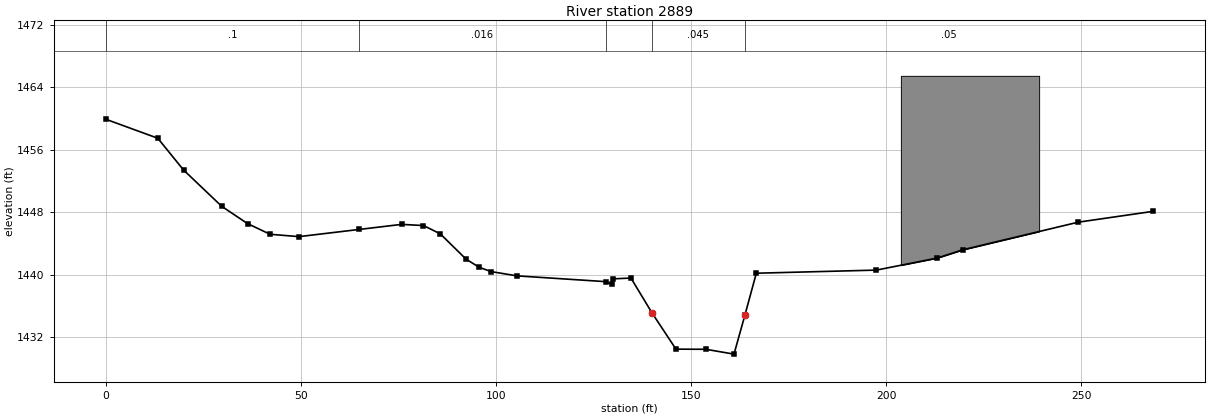
Type RM Length L Ch R = 1 ,2889    ,156.8,163,171.7
BEGIN DESCRIPTION:
Channel burned from survey ID: 54089BER038BD
END DESCRIPTION:
XS GIS Cut Line= 4
 1996090.2793537239684.9145622841996081.25297413239570.687435344
1996064.22293469239515.5079270721996069.67287103239419.590089566
#Sta/Elev= 30
       0 1459.91    13.3 1457.48    19.9 1453.41    29.7 1448.75    36.3 1446.54
    42.1 1445.17    49.5 1444.87    64.9 1445.79    75.8 1446.44    81.4 1446.29
    85.7 1445.23    92.3 1441.99    95.7 1440.93    98.8 1440.38   105.4 1439.84
   128.1  1439.1   129.6 1438.79     130 1439.46  134.58 1439.56  139.94 1435.12
  146.11 1430.45  153.77 1430.43  160.99 1429.81  163.77 1434.78  166.71 1440.18
   197.5 1440.58   213.1 1442.13   219.6 1443.18   249.2 1446.72   268.4 1448.11
#Mann= 5 ,-1 , 0
       0      .1       0    64.9    .016       0   128.1     .05       0
  139.94    .045       0  163.77     .05       0
#XS Ineff= 2 , 0
        137.3333  1435.8     165          1435.8
Permanent Ineff=
       F       F
#Block Obstruct= 1 ,-1
  203.76   239.2 1465.48
Bank Sta=139.94,163.77
XS Rating Curve= 0 ,0
Exp/Cntr(USF)=0,0
Exp/Cntr=0.5,0.3