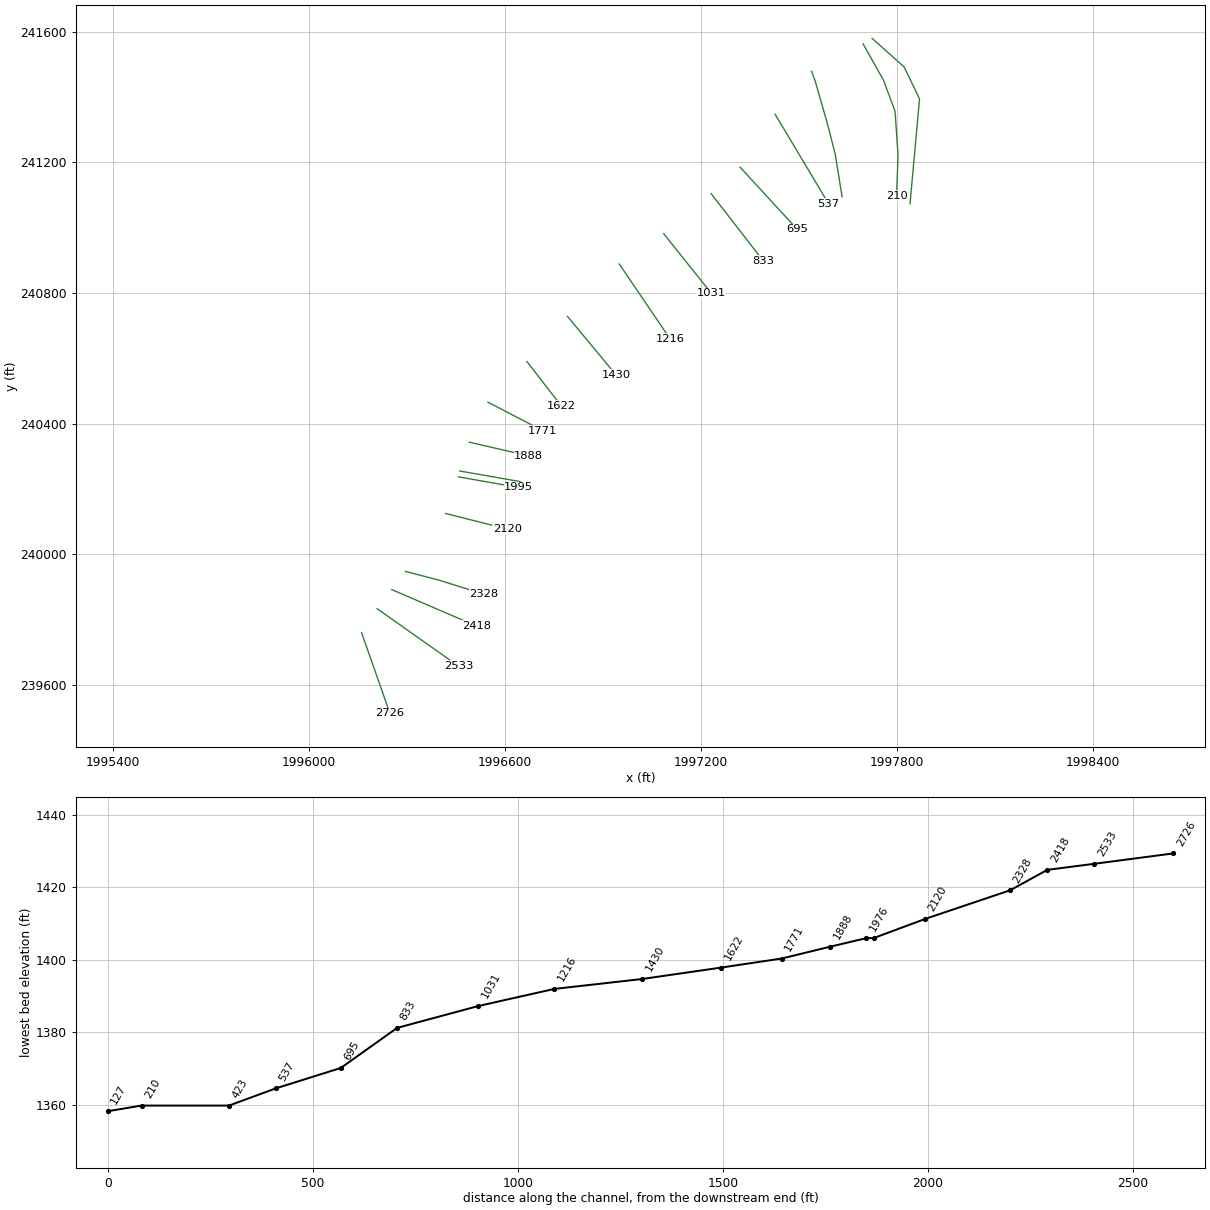
HEC-RAS study BEECHRN.prj: BEECHRN

--- BEECHRN.g01 (geometry) --- (continued)

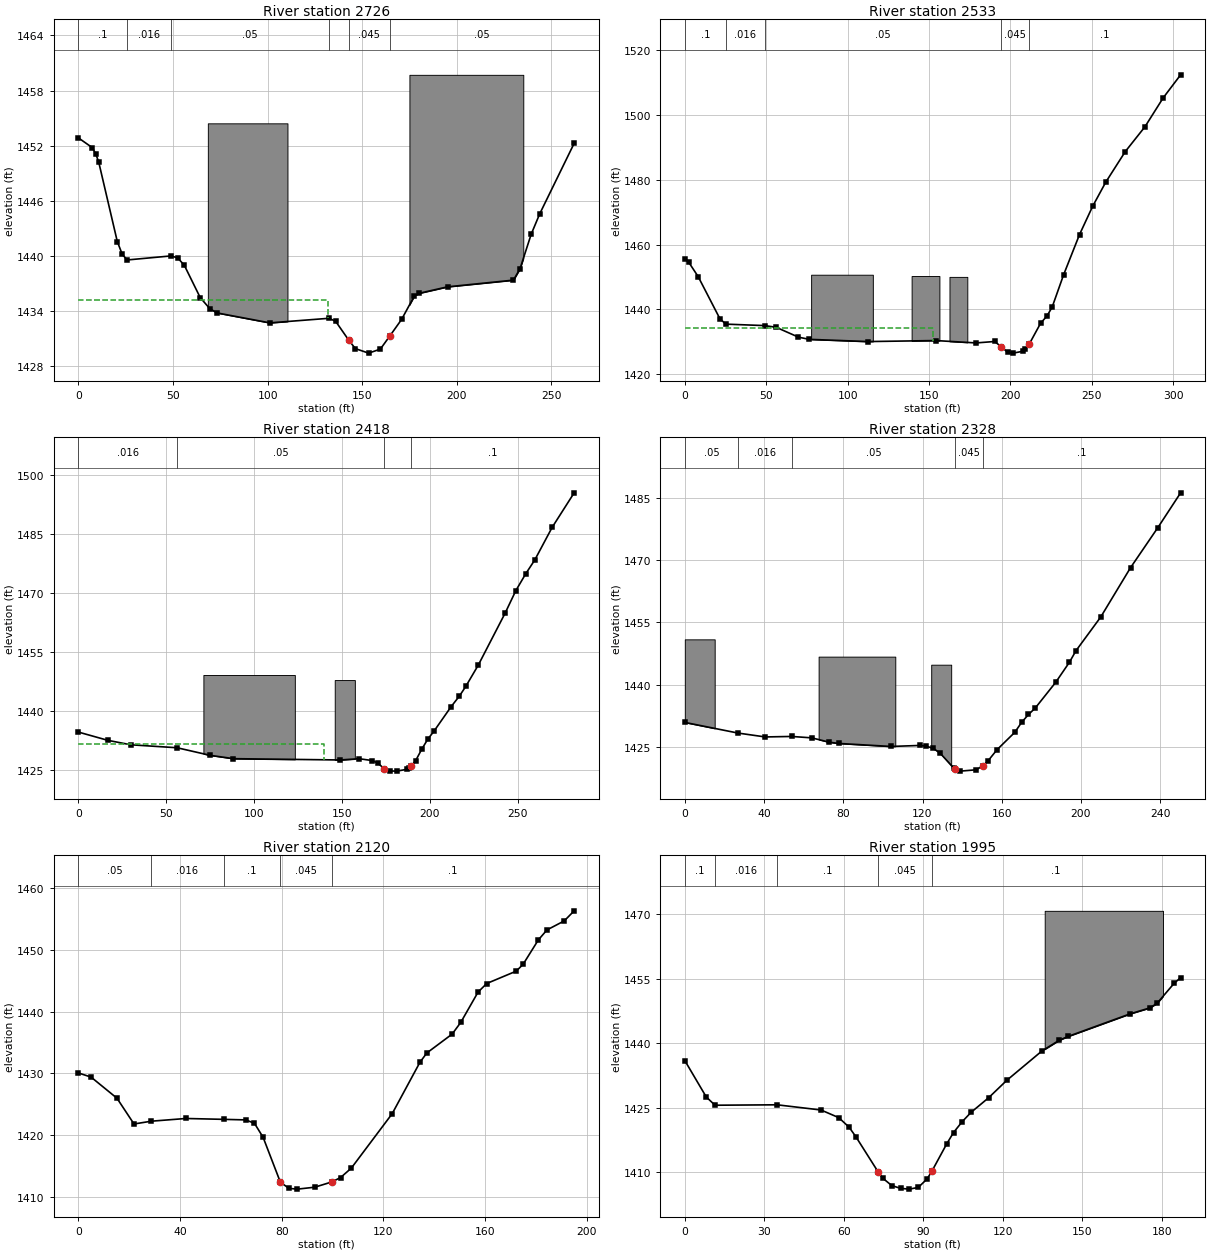
Type RM Length L Ch R = 1 ,2726    ,185.5,192.8,201
XS GIS Cut Line= 2
1996161.87293258239760.581030338 1996248.7925132239513.456732483
#Sta/Elev= 30
       0 1452.84     7.3 1451.78     9.2  1451.1    10.8 1450.17    20.6 1441.52
    23.2 1440.14    25.8 1439.52    48.9 1439.96    52.5 1439.75      56 1438.94
    64.4 1435.42    69.5  1434.2    73.4 1433.74   101.2 1432.66   132.5 1433.16
     136 1432.82   142.9 1430.77   146.4 1429.85   153.4 1429.36   159.6  1429.8
   164.7 1431.26   170.8 1433.03   177.6 1435.61   180.2 1435.89   195.1 1436.59
   229.9 1437.32   233.4 1438.57   239.3 1442.33   243.8 1444.55     262 1452.24
#Mann= 6 ,-1 , 0
       0      .1       0    25.8    .016       0    48.9     .05       0
   132.5      .1       0   142.9    .045       0   164.7     .05       0
#XS Ineff= 2 , 0
          131.83 1435.11
Permanent Ineff=
       F       F
#Block Obstruct= 2 ,-1
   68.43  110.51 1454.42  174.95  235.12 1459.71
Bank Sta=142.9,164.7
XS Rating Curve= 0 ,0
Exp/Cntr(USF)=0,0
Exp/Cntr=0.3,0.1

Type RM Length L Ch R = 1 ,2533    ,112.5,114.7,117.2
XS GIS Cut Line= 2
1996209.59348665239833.866166943   1996458.42209239658.322700191
#Sta/Elev= 30
       0 1455.69     2.5 1454.49     8.2 1450.13    21.6 1437.08    25.2 1435.45
      49    1435    56.1 1434.48    69.8 1431.43    76.5 1430.75   112.6 1430.07
   154.1 1430.38   178.9 1429.65   190.3 1430.09   194.3 1428.48   198.3 1426.75
   201.7  1426.5   207.4 1427.06   209.1 1427.64   211.4 1429.17   218.5 1435.72
   222.4 1437.95   225.6  1440.7   232.6 1450.64   242.4  1463.1   250.5 1471.86
   258.5 1479.26   270.5 1488.72   282.6 1496.39   293.8 1505.32   304.5 1512.42
#Mann= 5 ,-1 , 0
       0      .1       0    25.2    .016       0      49     .05       0
   194.3    .045       0   211.4      .1       0
#XS Ineff= 2 , 0
          152.62 1434.32
Permanent Ineff=
       F       F
#Block Obstruct= 3 ,-1
   77.58  115.48 1450.71  139.29  156.36  1450.3  162.54   173.5 1450.04
Bank Sta=194.3,211.4
XS Rating Curve= 0 ,0
Exp/Cntr(USF)=0,0
Exp/Cntr=0.3,0.1

Type RM Length L Ch R = 1 ,2418    ,89.5,90.5,91.7
XS GIS Cut Line= 2
1996254.37933076239892.3443134261996513.63996833239780.825609041
#Sta/Elev= 30
       0 1434.73    16.9 1432.62    29.9  1431.5    56.2 1430.75    74.9 1428.84
    88.3 1427.98     149 1427.65   159.8 1427.97   167.3  1427.5   170.5 1426.84
     174 1425.47   177.6 1424.85   181.2 1424.82   187.3  1425.3   188.3 1425.49
   189.41426.047   191.9 1427.41   195.5 1430.41     199    1433   202.3 1434.88
   212.2 1441.19   216.9 1443.87   220.5  1446.3   227.6 1451.69   242.9 1464.89
     249 1470.61   254.7 1474.93   259.8  1478.4   269.7 1486.68   282.2 1495.42
#Mann= 4 ,-1 , 0
       0    .016       0    56.2     .05       0     174    .045       0
   189.4      .1       0
#XS Ineff= 2 , 0
             140 1431.66
Permanent Ineff=
       F       F
#Block Obstruct= 2 ,-1
   71.18  123.22 1449.21  145.93  157.38 1447.92
Bank Sta=174,189.4
XS Rating Curve= 0 ,0
Exp/Cntr(USF)=0,0
Exp/Cntr=0.3,0.1

Type RM Length L Ch R = 1 ,2328    ,206.7,207.4,208.3
XS GIS Cut Line= 3
1996296.51306727239948.0546356071996400.47570292239920.785747568
1996536.82014311239878.178110006
#Sta/Elev= 30
       0 1430.93    26.8 1428.37    40.6 1427.43    53.9 1427.55    64.1 1427.21
    72.9 1426.17    77.6 1425.87   104.1 1425.14   118.5 1425.38   121.9 1425.22
   125.4 1424.68   128.8 1423.57   135.7 1419.95   136.6  1419.7   139.1  1419.2
   147.1 1419.52   150.7 1420.55   152.9 1421.57   157.6 1424.35   166.6 1428.55
     170 1430.92   173.5 1432.84   176.9 1434.38   187.2 1440.56   194.1 1445.37
   197.5 1448.21     210 1456.33     225 1468.18   238.8 1477.83   250.3 1486.21
#Mann= 5 ,-1 , 0
       0     .05       0    26.8    .016       0    53.9     .05       0
   136.6    .045       0   150.7      .1       0
#Block Obstruct= 3 ,-1
       0   15.09 1450.93   67.55  106.26 1446.77  124.39  134.48 1444.83
Bank Sta=136.6,150.7
XS Rating Curve= 0 ,0
Exp/Cntr(USF)=0,0
Exp/Cntr=0.3,0.1

Type RM Length L Ch R = 1 ,2120    ,124.4,125.4,126.7
XS GIS Cut Line= 2
1996419.22306345240125.3024078611996608.40097422240077.581853792
#Sta/Elev= 30
       0 1430.09       5 1429.42    15.2    1426    21.9 1421.83    28.7 1422.28
    42.3 1422.72    57.2 1422.58    65.9 1422.49    69.3 1421.94    72.7 1419.68
    79.5 1412.41    82.9 1411.41    86.2 1411.29      93  1411.6    99.8 1412.46
   103.2 1413.17   107.4 1414.68   123.5  1423.5   134.4  1431.8   137.1 1433.31
   147.1 1436.38   150.5 1438.28   157.3 1443.18   160.7 1444.56   172.3 1446.56
     175 1447.66     181 1451.61   184.4 1453.23   191.2 1454.69   195.1 1456.32
#Mann= 5 ,-1 , 0
       0     .05       0    28.7    .016       0    57.2      .1       0
    79.5    .045       0    99.8      .1       0
#Block Obstruct= 2 , 0
            9.51 1450.09
Bank Sta=79.5,99.8
XS Rating Curve= 0 ,0
Exp/Cntr(USF)=0,0
Exp/Cntr=0.5,0.3

Type RM Length L Ch R = 1 ,1995    ,18.4,18.4,18.4
XS GIS Cut Line= 2
  1996458.759893240237.4365165851996643.07377176 240205.10074838
#Sta/Elev= 30
       0 1435.93     8.1 1427.45    11.4 1425.53    34.8 1425.63    51.4 1424.42
    58.1 1422.64      62 1420.42    64.6 1418.16    72.9 1410.07    74.7 1408.55
    78.1 1406.84    81.4 1406.19    84.7 1406.01    88.1 1406.41    91.4 1408.36
    93.2 1410.14    98.8  1416.5   101.4 1419.18   104.7 1421.72     108 1423.86
   114.7  1427.3   121.5 1431.32   134.7 1438.12   141.3 1440.65   144.7 1441.55
     168 1446.78   175.4 1448.16   178.2 1449.23   184.7 1453.93   187.1 1455.21
#Mann= 5 ,-1 , 0
       0      .1       0    11.4    .016       0    34.8      .1       0
    72.9    .045       0    93.2      .1       0
#XS Ineff= 2 , 0
              52 1422.08     116         1422.08
Permanent Ineff=
       F       F
#Block Obstruct= 1 ,-1
  135.81  180.45 1470.76
Bank Sta=72.9,93.2
XS Rating Curve= 0 ,0
Exp/Cntr(USF)=0,0
Exp/Cntr=0.5,0.3

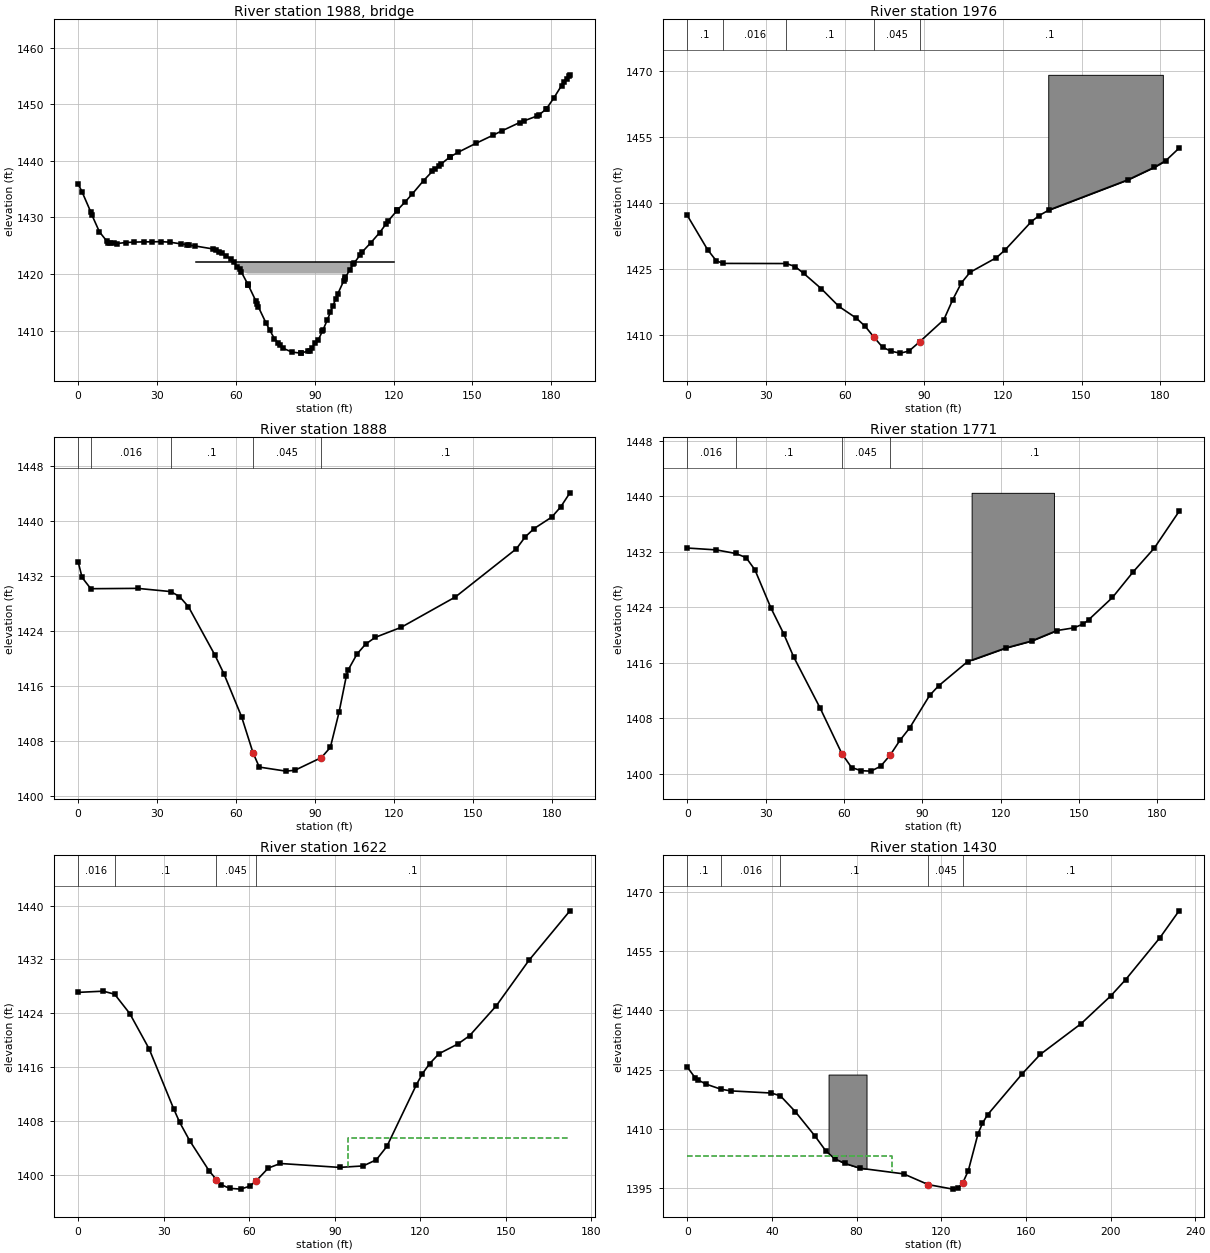
Type RM Length L Ch R = 3 ,1988    ,,,
BEGIN DESCRIPTION:
Private Driveway
Road deck determined from Lidar and bridge opened determined by imagery
END DESCRIPTION:
Bridge Culvert--1,0,-1,-1, 0
Deck Dist Width WeirC Skew NumUp NumDn MinLoCord MaxHiCord MaxSubmerge Is_Ogee
2,8,2.6,0, 6, 6, , , 0.98, 0, 0,0,,
      45      54      54     114     114     120
 1422.08 1422.08 1422.08 1422.08 1422.08 1422.08
                 1420.08 1420.08
      45      54      54     114     114     120
 1422.08 1422.08 1422.08 1422.08 1422.08 1422.08
                 1420.08 1420.08
BR Coef=-1 , 1 , 0 ,, 0 ,,,0.8,0,1.2,0,
WSPro=,,,, 1 ,,,, 0 ,,,, 0 ,,,,-1 ,-1 ,-1 , 0 , 0 , 0 , 0 , 0
BR U #Sta/Elev= 97
       0 1435.93     1.5 1434.51     4.8 1430.98     5.3 1430.37     8.1 1427.45
      11 1425.76    11.4 1425.53    12.1 1425.51    13.8  1425.4    14.8 1425.39
    18.1 1425.56    21.4 1425.64    25.2 1425.68    28.1 1425.68    31.4 1425.72
    34.8 1425.63    39.3 1425.31    41.4 1425.18    42.2 1425.11    44.4 1424.96
    51.4 1424.42    52.5 1424.21    53.5 1423.93    54.7 1423.72    56.3 1423.17
    58.1 1422.64    59.2 1422.08    60.6 1421.29    61.4 1420.85      62 1420.42
    64.6 1418.16    64.7 1418.06    64.8 1417.97    67.7 1415.15    68.1 1414.72
    68.6 1414.15    71.4 1411.41    72.9 1410.07    74.7 1408.55    76.2  1407.8
    76.7 1407.53    78.1 1406.84    81.4 1406.19    84.7 1406.01    84.8 1406.01
    87.5  1406.4    88.1 1406.41    88.8 1406.85    90.3 1407.83    91.4 1408.36
    92.9 1409.88    93.2 1410.14    94.7 1411.79      96 1413.23    96.9 1414.36
    98.1 1415.66    98.8  1416.5     101 1418.74   101.4 1419.18   101.7 1419.42
   103.3 1420.71   104.7 1421.72     105 1421.91   107.3 1423.39     108 1423.86
   111.4 1425.55   114.7  1427.3   117.1 1428.83     118  1429.4   121.2 1431.15
   121.4 1431.26   121.5 1431.32   124.3 1432.69   127.2 1434.19   131.4  1436.5
   134.7 1438.12   135.7 1438.49   137.3 1439.14     138 1439.41   141.3 1440.64
   141.3 1440.65   144.7 1441.55   151.3 1443.09     158 1444.57   161.2  1445.3
     168 1446.78   169.7 1447.08   174.7 1447.95   175.4 1448.16     178 1449.12
   178.2 1449.23     181 1451.13   183.9  1453.3   184.7 1453.93   185.8  1454.5
   186.7    1455   187.1 1455.21
BR U #Mann= 5
       0      .1    11.4    .016    34.8      .1    72.9     .04    93.2      .1
BR D #Sta/Elev= 97
       0 1437.27      .7 1436.78       1 1436.51     3.5 1433.79     4.4 1432.89
     7.7 1429.51      11 1426.98      12 1426.71    13.6 1426.36    14.4 1426.18
    17.7 1426.35      21 1426.47    23.4 1426.47    27.7 1426.51      31 1426.52
    34.3 1426.49    37.7 1426.33      41 1425.65    44.3 1424.09    48.9 1421.71
      51 1420.61    54.3 1418.54    55.7 1417.72    57.4 1416.74    57.7 1416.58
    60.2 1415.59    62.1 1414.81      63 1414.46    64.3 1413.93    67.7 1412.06
      71 1409.62    74.3 1407.32    77.6  1406.4      81 1405.98    82.3 1406.16
    82.9 1406.17    84.3 1406.43    85.7 1407.06    86.4 1407.44    87.6 1408.08
    88.5  1408.6    90.4 1409.77      91 1410.12    91.4 1410.25    93.7 1411.35
    94.2 1411.57    94.3 1411.63    94.4 1411.72      97 1413.11    97.6 1413.56
    98.5 1414.69    99.9 1416.71     101 1418.13   102.7 1420.19   104.3 1421.95
   105.5 1422.95   106.5 1423.55   107.6 1424.35   108.4 1424.62     111 1425.48
     114 1426.36   116.9 1427.38   117.6 1427.66   120.9 1429.41   124.3 1431.68
   125.4 1432.41   126.7 1433.32   127.6 1433.89   130.9 1435.85     131  1435.9
   131.7 1436.19   133.9 1437.24   134.3 1437.41   137.6 1438.49   140.9  1439.2
   142.4 1439.57   144.3 1440.03   145.2 1440.24   146.9 1440.58   150.6 1441.38
   157.6    1443   162.2 1444.07   167.6 1445.34   170.7 1446.28   170.9 1446.34
   171.2 1446.42   173.6 1447.11   174.2 1447.29   175.2 1447.55   176.4 1447.87
   177.6 1448.17   180.9 1449.19   182.1 1449.73   183.3 1450.37   184.2 1450.82
   184.9 1451.18   187.1 1452.54
BR D #Mann= 5
       0      .1    13.6    .016    37.7      .1      71     .04    88.5      .1
BC Design=,, 0 ,, 0 ,,,,,,
BC Use User HTab Curves=0
BC User HTab FreeFlow(D)= 0

Type RM Length L Ch R = 1 ,1976    ,88.8,88.2,87.2
XS GIS Cut Line= 2
1996462.45540937 240255.452158871996646.76928813240223.116390666
#Sta/Elev= 30
       0 1437.27     7.7 1429.51      11 1426.98    13.6 1426.36    37.7 1426.33
      41 1425.65    44.3 1424.09      51 1420.61    57.7 1416.58    64.3 1413.93
    67.7 1412.06      71 1409.62    74.3 1407.32    77.6  1406.4      81 1405.98
    84.3 1406.43    88.5  1408.6    97.6 1413.56     101 1418.13   104.3 1421.95
   107.6 1424.35   117.6 1427.66   120.9 1429.41   130.9 1435.85   133.9 1437.24
   137.6 1438.49   167.6 1445.34   177.6 1448.17   182.1 1449.73   187.1 1452.54
#Mann= 5 ,-1 , 0
       0      .1       0    13.6    .016       0    37.7      .1       0
      71    .045       0    88.5      .1       0
#XS Ineff= 2 , 0
        50.66667 1420.08117.3333         1420.08
Permanent Ineff=
       F       F
#Block Obstruct= 1 ,-1
  137.33  180.93  1469.2
Bank Sta=71,88.5
XS Rating Curve= 0 ,0
Exp/Cntr(USF)=0,0
Exp/Cntr=0.5,0.3

Type RM Length L Ch R = 1 ,1888    ,119.7,117.7,113.6
XS GIS Cut Line= 2
1996491.55760075240343.6826121131996673.56178179240301.646113448
#Sta/Elev= 30
       0 1434.08     1.5  1431.8     4.8 1430.16    22.6 1430.21    35.2 1429.74
    38.5 1429.02    41.9 1427.54      52 1420.47    55.4 1417.76    62.1 1411.52
    66.4 1406.32    68.8 1404.21    78.9 1403.62    82.3 1403.74    92.4 1405.59
    95.8 1407.07    99.1 1412.18   101.9 1417.51   102.5 1418.29   105.9 1420.64
   109.2  1422.1   112.9 1423.09   122.7 1424.54   143.3 1428.96   166.5 1435.98
   169.8 1437.69   173.2 1438.91   179.9 1440.58   183.3 1442.06   186.8 1444.11
#Mann= 5 ,-1 , 0
       0      .1       0     4.8    .016       0    35.2      .1       0
    66.4    .045       0    92.4      .1       0
Bank Sta=66.4,92.4
XS Rating Curve= 0 ,0
Exp/Cntr(USF)=0,0
Exp/Cntr=0.3,0.1

Type RM Length L Ch R = 1 ,1771    ,152.2,148.3,142.9
XS GIS Cut Line= 2
1996548.75028163 240466.163508351996715.77222087240379.243927725
#Sta/Elev= 30
       0 1432.54    11.1 1432.27    18.5 1431.76    22.5 1431.17    25.9  1429.4
      32 1423.92    36.9 1420.19    40.7 1416.87    50.9 1409.44    59.2 1402.89
    62.9 1400.89    66.6 1400.43    70.3 1400.37      74 1401.06    77.7 1402.68
    81.4  1404.8    85.1 1406.57    92.8 1411.29    96.2 1412.66   107.3 1416.15
   121.9 1418.12   131.8 1419.13   141.5 1420.64     148 1421.03   151.7  1421.6
   153.7  1422.2   162.8 1425.41   170.7 1429.09   178.8 1432.52   188.3 1437.82
#Mann= 4 ,-1 , 0
       0    .016       0    18.5      .1       0    59.2    .045       0
    77.7      .1       0
#Block Obstruct= 1 ,-1
  108.87  140.39  1440.5
Bank Sta=59.2,77.7
XS Rating Curve= 0 ,0
Exp/Cntr(USF)=0,0
Exp/Cntr=0.3,0.1

Type RM Length L Ch R = 1 ,1622    ,192.7,192.8,193.9
XS GIS Cut Line= 2
 1996668.0516668240590.5778100281996773.71860795240454.233369833
#Sta/Elev= 30
       0  1427.1     8.8 1427.28    12.8 1426.83    18.1 1423.96    24.9 1418.71
    33.5 1409.81    35.6  1407.8    39.1 1405.08      46 1400.54    48.5 1399.29
    50.1 1398.54    53.1 1397.98      57 1397.86    60.2  1398.3    62.5 1399.11
    66.7 1400.99    70.9 1401.67    91.7 1401.09     100 1401.31   104.6 1402.22
   108.3 1404.21   118.6 1413.33   120.7 1414.98   123.3 1416.51   126.6 1417.99
   133.2 1419.43   137.3 1420.66   146.7 1425.12   158.1 1431.85   172.5 1439.22
#Mann= 4 ,-1 , 0
       0    .016       0    12.8      .1       0    48.5    .045       0
    62.5      .1       0
#XS Ineff= 2 , 0
                           94.51         1405.39
Permanent Ineff=
       F       F
Bank Sta=48.5,62.5
XS Rating Curve= 0 ,0
Exp/Cntr(USF)=0,0
Exp/Cntr=0.3,0.1

Type RM Length L Ch R = 1 ,1430    ,214.6,213.6,212.2
XS GIS Cut Line= 2
1996792.46596848240728.6265557261996940.74054719 240549.67447797
#Sta/Elev= 30
       0 1425.63     3.7 1422.92     4.9 1422.42     8.9  1421.3      16    1420
    20.7 1419.59    39.7 1419.05      44 1418.34      51 1414.37    60.3 1408.19
    65.4 1404.44    69.6 1402.41    74.3 1401.25    81.6 1400.01   102.2 1398.58
   113.9 1395.85   125.5 1394.71   127.9 1394.91   130.2  1396.3   132.8 1399.38
   137.4 1408.73   139.5  1411.4   141.9 1413.54   158.3 1423.93   166.8 1428.83
   186.1 1436.61   200.1 1443.64   207.1 1447.74   223.4 1458.42   232.4  1465.2
#Mann= 5 ,-1 , 0
       0      .1       0      16    .016       0      44      .1       0
   113.9    .045       0   130.2      .1       0
#XS Ineff= 2 , 0
           96.62 1403.07
Permanent Ineff=
       F       F
#Block Obstruct= 1 ,-1
   66.77   84.71 1423.73
Bank Sta=113.9,130.2
XS Rating Curve= 0 ,0
Exp/Cntr(USF)=0,0
Exp/Cntr=0.3,0.1

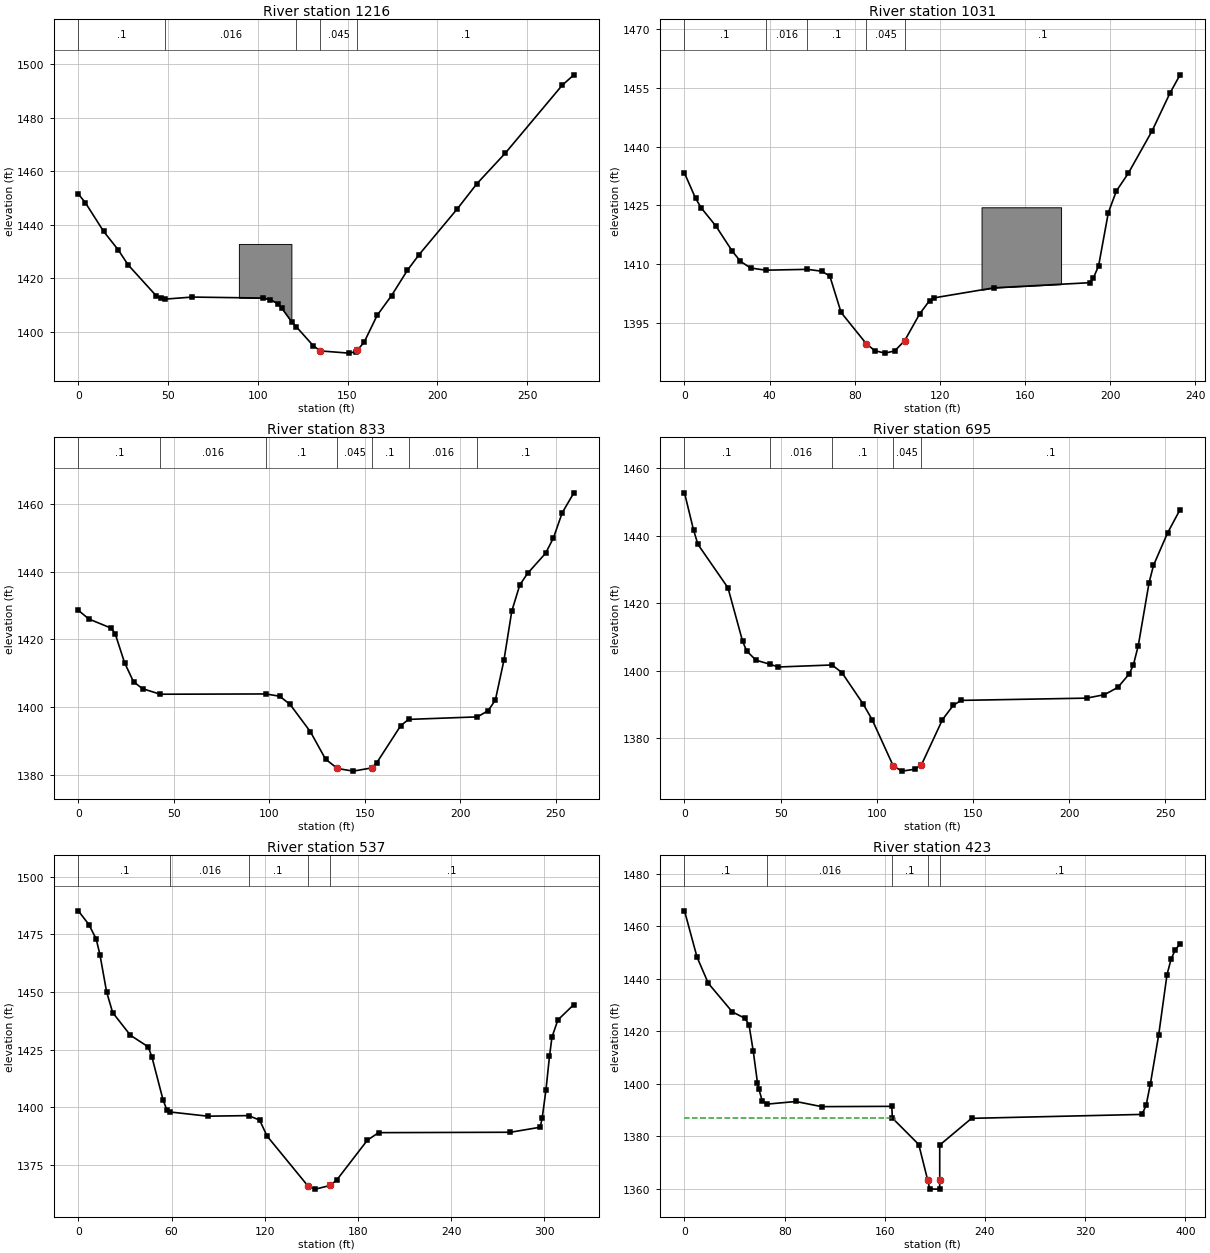
Type RM Length L Ch R = 1 ,1216    ,181.7,185,184.5
XS GIS Cut Line= 2
1996950.96638021240888.8312729561997106.05818093240660.454335628
#Sta/Elev= 30
       0 1451.51     3.9 1448.28    14.1 1437.52    22.2 1430.64    27.7 1425.03
    43.3  1413.5    45.8 1412.52    48.2 1412.18    63.4 1412.95   103.1 1412.58
     107 1411.96     111 1410.54   113.4 1408.75   118.9 1403.66   121.4 1401.88
   130.8 1394.82   134.8 1392.81   150.7 1391.98   154.5 1392.48   155.4 1393.06
   159.2 1396.01   166.5 1406.11   174.5 1413.49   183.4 1423.02   189.9 1428.86
   211.2 1445.99     222  1455.3   237.9  1466.8   269.6 1492.19   276.1 1496.09
#Mann= 5 ,-1 , 0
       0      .1       0    48.2    .016       0   121.4      .1       0
   134.8    .045       0   155.4      .1       0
#Block Obstruct= 1 ,-1
   89.45  118.72 1432.83
Bank Sta=134.8,155.4
XS Rating Curve= 0 ,0
Exp/Cntr(USF)=0,0
Exp/Cntr=0.3,0.1

Type RM Length L Ch R = 1 ,1031    ,197,198,196.5
XS GIS Cut Line= 2
1997086.84098169240981.8681204031997232.14978158240799.849728955
#Sta/Elev= 30
       0 1433.24     5.2 1426.82     7.8  1424.4    14.8 1419.69    22.4 1413.35
    26.3 1410.71    31.1    1409    38.2 1408.45    57.8 1408.66    64.4 1408.19
    68.3 1406.96    73.6 1397.66    85.4  1389.7    89.4  1387.9    94.2 1387.27
    98.8 1387.83   103.5 1390.46   110.5 1397.26   115.2  1400.7   117.5  1401.4
   145.5 1403.95   190.4 1405.25   192.2 1406.52   194.6 1409.49   199.2 1423.14
     203 1428.69   208.6 1433.21   219.8 1444.05   228.1 1453.59   232.9 1458.33
#Mann= 5 ,-1 , 0
       0      .1       0    38.2    .016       0    57.8      .1       0
    85.4    .045       0   103.5      .1       0
#Block Obstruct= 1 ,-1
  139.61  176.99 1424.51
Bank Sta=85.4,103.5
XS Rating Curve= 0 ,0
Exp/Cntr(USF)=0,0
Exp/Cntr=0.3,0.1

Type RM Length L Ch R = 1 ,833     ,135.2,137.5,138.7
XS GIS Cut Line= 2
1997232.14978158241104.2334255791997391.22467831 240899.27153941
#Sta/Elev= 30
       0 1428.59     5.5 1426.03    17.2 1423.33    19.3 1421.69    24.2 1413.17
    28.9 1407.55    33.6 1405.51    42.9 1403.88    98.2 1403.96   105.4 1403.29
   110.8 1400.91   121.5 1392.82   129.4 1384.78   135.6 1382.02   143.9 1381.24
   153.6 1382.19   156.3 1383.77   168.8 1394.65   172.9 1396.47   208.9 1397.21
   214.5 1399.02   218.3 1402.16   222.8  1413.9   226.9 1428.35   231.1 1436.07
   235.2 1439.47   244.6 1445.39   248.7 1449.89   253.3 1457.31   259.4 1463.17
#Mann= 7 ,-1 , 0
       0      .1       0    42.9    .016       0    98.2      .1       0
   135.6    .045       0   153.6      .1       0   172.9    .016       0
   208.9      .1       0
Bank Sta=135.6,153.6
XS Rating Curve= 0 ,0
Exp/Cntr(USF)=0,0
Exp/Cntr=0.3,0.1

Type RM Length L Ch R = 1 ,695     ,159.7,158.8,155.3
XS GIS Cut Line= 2
1997320.86462784241185.3004402581997495.23518771240995.634217236
#Sta/Elev= 30
       0 1452.76     4.7 1441.75       7 1437.45    22.6 1424.58    30.2 1408.74
    32.3 1405.85    37.2 1403.09    44.2 1401.94    48.8 1401.08    76.7 1401.68
    81.8 1399.44    92.9 1390.08    97.6  1385.4   108.5 1371.74     113 1370.18
   119.6 1370.73   123.1 1371.95   134.1 1385.46   139.7 1389.69   143.8 1391.17
     209 1391.84   218.3 1392.86   225.3 1395.04   231.1 1398.97   233.3 1401.59
   235.9 1407.45   241.5 1426.09   243.8 1431.23   251.1 1440.83   257.6 1447.77
#Mann= 5 ,-1 , 0
       0      .1       0    44.2    .016       0    76.7      .1       0
   108.5    .045       0   123.1      .1       0
Bank Sta=108.5,123.1
XS Rating Curve= 0 ,0
Exp/Cntr(USF)=0,0
Exp/Cntr=0.3,0.1

Type RM Length L Ch R = 1 ,537     ,116.7,113.7,108.6
XS GIS Cut Line= 2
1997427.93426987241347.4344696151997591.59786554241073.642099285
#Sta/Elev= 30
       0 1485.17     6.8 1479.21    11.5 1472.96    13.9 1466.21    18.2 1450.07
    22.1 1441.07    33.5 1431.26      45 1426.21    47.4 1421.77    54.5 1403.33
    56.9    1399    59.3 1397.96    83.3 1396.16   109.6 1396.41   116.7 1394.47
   121.5 1387.54   147.8 1365.92   152.6 1364.54   162.2 1366.15   166.5 1368.62
   186.1 1385.77   193.3 1389.02   278.2 1389.19   297.3 1391.37   298.6 1395.34
     301 1407.39   303.3 1422.06   304.9 1430.42   308.7 1437.86     319 1444.56
#Mann= 5 ,-1 , 0
       0      .1       0    59.3    .016       0   109.6      .1       0
   147.8    .045       0   162.2      .1       0
Bank Sta=147.8,162.2
XS Rating Curve= 0 ,0
Exp/Cntr(USF)=0,0
Exp/Cntr=0.5,0.3

Type RM Length L Ch R = 1 ,423     ,213,213.3,223.7
BEGIN DESCRIPTION:
Channel burned from survey ID: 54089BER012CU
END DESCRIPTION:
XS GIS Cut Line= 5
1997539.59261084241478.9771726791997550.29957504  241449.9154127
1997586.31776392241324.7579954761997611.90130945241225.621756551
1997632.89615603241095.056027691
#Sta/Elev= 30
       0 1465.85      10 1448.24      19 1438.25    38.2 1427.34    48.1 1424.95
    51.5 1422.51    54.9 1412.44    58.3 1400.33    59.4 1397.98    62.1 1393.42
    65.8 1392.19      89  1393.2   109.5 1391.24   165.6 1391.35     166 1386.91
  187.11 1376.81  194.15 1363.42  195.95 1359.84  203.79 1359.81  203.85 1363.42
  203.86  1376.6  229.28 1386.78   365.4 1388.28   368.7 1391.71   372.1  1399.9
   378.7 1418.43   385.4 1441.55   388.7 1447.52     392 1450.96   395.8 1453.26
#Mann= 5 ,-1 , 0
       0      .1       0    65.8    .016       0     166      .1       0
  194.15    .045       0  203.85      .1       0
#XS Ineff= 2 , 0
             168 1387.06     239         1386.31
Permanent Ineff=
       F       F
Bank Sta=194.15,203.85
XS Rating Curve= 0 ,0
Exp/Cntr(USF)=0,0
Exp/Cntr=0.5,0.3

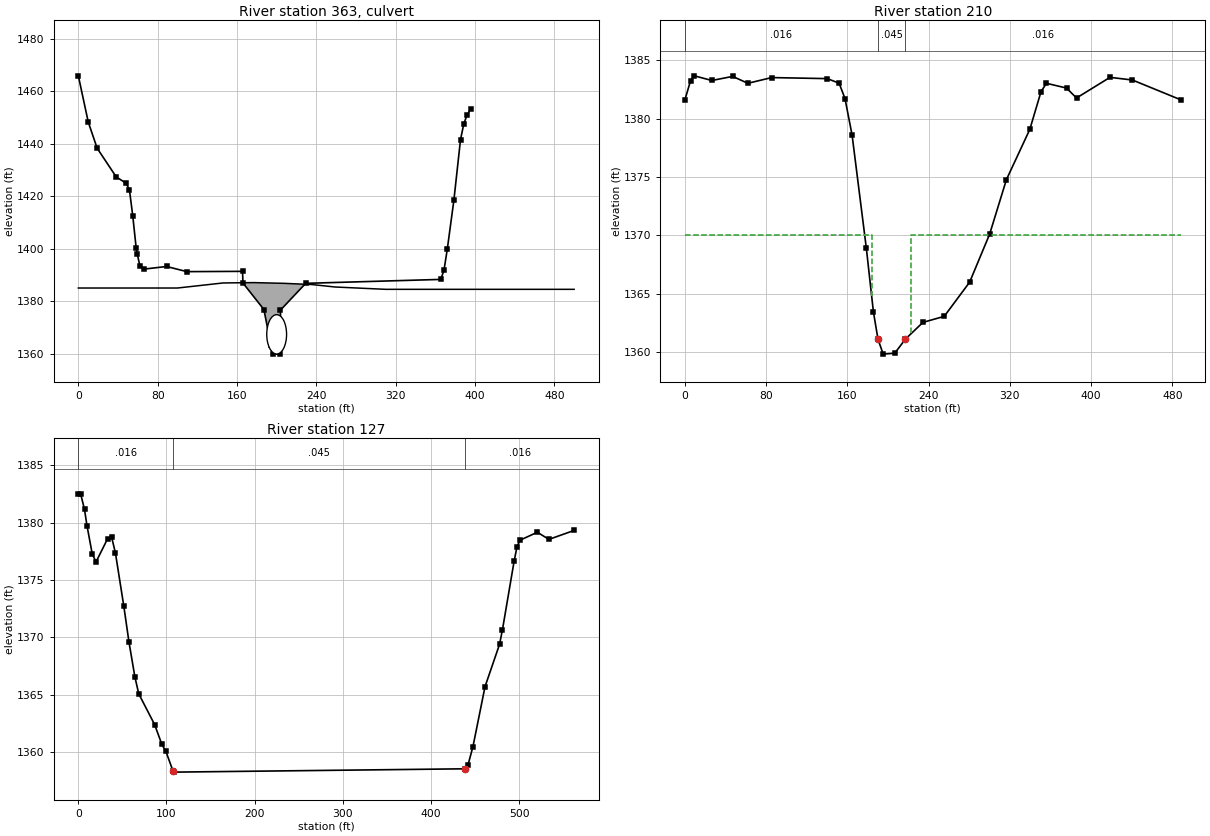
Type RM Length L Ch R = 2 ,363     ,,,
BEGIN DESCRIPTION:
Hinton Bypass
Survey ID: BER010
Ellipse shape only allows for concert chart. The entrance loss and mannings represent the corregated metal material
END DESCRIPTION:
Bridge Culvert--1,0,-1,-1, 0
Deck Dist Width WeirC Skew NumUp NumDn MinLoCord MaxHiCord MaxSubmerge Is_Ogee
34,53,2.6,0, 9, 9, , , 0.98, 0, 0,0,,
       0     100     146     177     208     236     259     310     500
    1385    13851386.9271387.0591386.7791386.3071385.383  1384.5  1384.5
                                                                        
       0     100     146     177     208     236     259     310     500
    1385    13851386.9271387.0591386.7791386.3071385.383  1384.5  1384.5
                                                                        
BR Coef=-1 , 1 , 0 ,, 0 ,,,0.8,0,1.2,0,
WSPro=,,,, 1 ,,,, 0 ,,,, 0 ,,,,-1 ,-1 ,-1 , 0 , 0 , 0 , 0 , 0
Culvert=4,15,20,185,0.019,0.5,1,29,1,1359.845,200,1359.816,200,Culvert #1  , 2 ,16
     200     200
BC Culvert Barrel=1,Barrel1,0
Culvert Bottom n=0.019
BC Design=,, 0 ,, 0 ,,,,,,
BC Use User HTab Curves=0
BC User HTab FreeFlow(D)= 0

Type RM Length L Ch R = 1 ,210     ,117.2,82.6,173.3
BEGIN DESCRIPTION:
Channel invert is determined by 54089BER008CD
END DESCRIPTION:
XS GIS Cut Line= 5
1997697.13794125241563.1033199871997759.85016015241451.444979014
1997795.03018539241356.6118675031997804.20758328 241222.01003181
1997799.61888434 241098.11516032
#Sta/Elev= 30
       0 1381.58     5.7 1383.26     9.4 1383.67    26.6 1383.27    47.1 1383.62
    62.1 1383.03    85.5 1383.52   140.2 1383.43   151.9 1383.04   157.7 1381.72
   164.7 1378.58   178.7  1368.9   185.7 1363.42   190.2 1361.08   195.3 1359.81
   206.7 1359.89   217.2  1361.1   234.4 1362.53   255.4 1363.05   280.4 1365.98
   300.1  1370.1   316.6 1374.77   339.6 1379.07   350.7 1382.32     356 1383.03
   375.8 1382.62   385.6 1381.77   418.6 1383.54   440.7 1383.31   488.1 1381.62
#Mann= 3 ,-1 , 0
       0    .016       0   190.2    .045       0   217.2    .016       0
#XS Ineff= 2 , 0
             184    1370     223            1370
Permanent Ineff=
       F       F
Bank Sta=190.2,217.2
XS Rating Curve= 0 ,0
Exp/Cntr(USF)=0,0
Exp/Cntr=0.5,0.3

Type RM Length L Ch R = 1 ,127     ,,,
XS GIS Cut Line= 4
1997724.67013492241579.9285494491997822.56237906241492.743269511
1997869.97893481241394.8510253711997840.91717483241073.642099285
#Sta/Elev= 30
       0 1382.46     2.6 1382.51       7 1381.15     9.8 1379.74    15.8 1377.26
    20.1 1376.58    33.3 1378.61    37.7 1378.76    42.1 1377.34    51.6 1372.71
    57.4 1369.61    64.1 1366.57    68.5 1365.08    86.5  1362.4    94.8 1360.66
    99.2 1360.08   107.4 1358.34     108 1358.25     439 1358.54     442 1358.88
   447.6 1360.47   461.3  1365.7   477.8  1369.4   481.1 1370.68   494.3 1376.64
   497.5 1377.87   500.8 1378.46   520.6 1379.16   533.8 1378.54   562.4 1379.32
#Mann= 3 ,-1 , 0
       0    .016       0   107.4    .045       0     439    .016       0
Bank Sta=107.4,439
XS Rating Curve= 0 ,0
Exp/Cntr(USF)=0,0
Exp/Cntr=0.3,0.1
LCMann Table=0

Chan Stop Cuts=-1
Use User Specified Reach Order=0
Composite Channel Slope=5